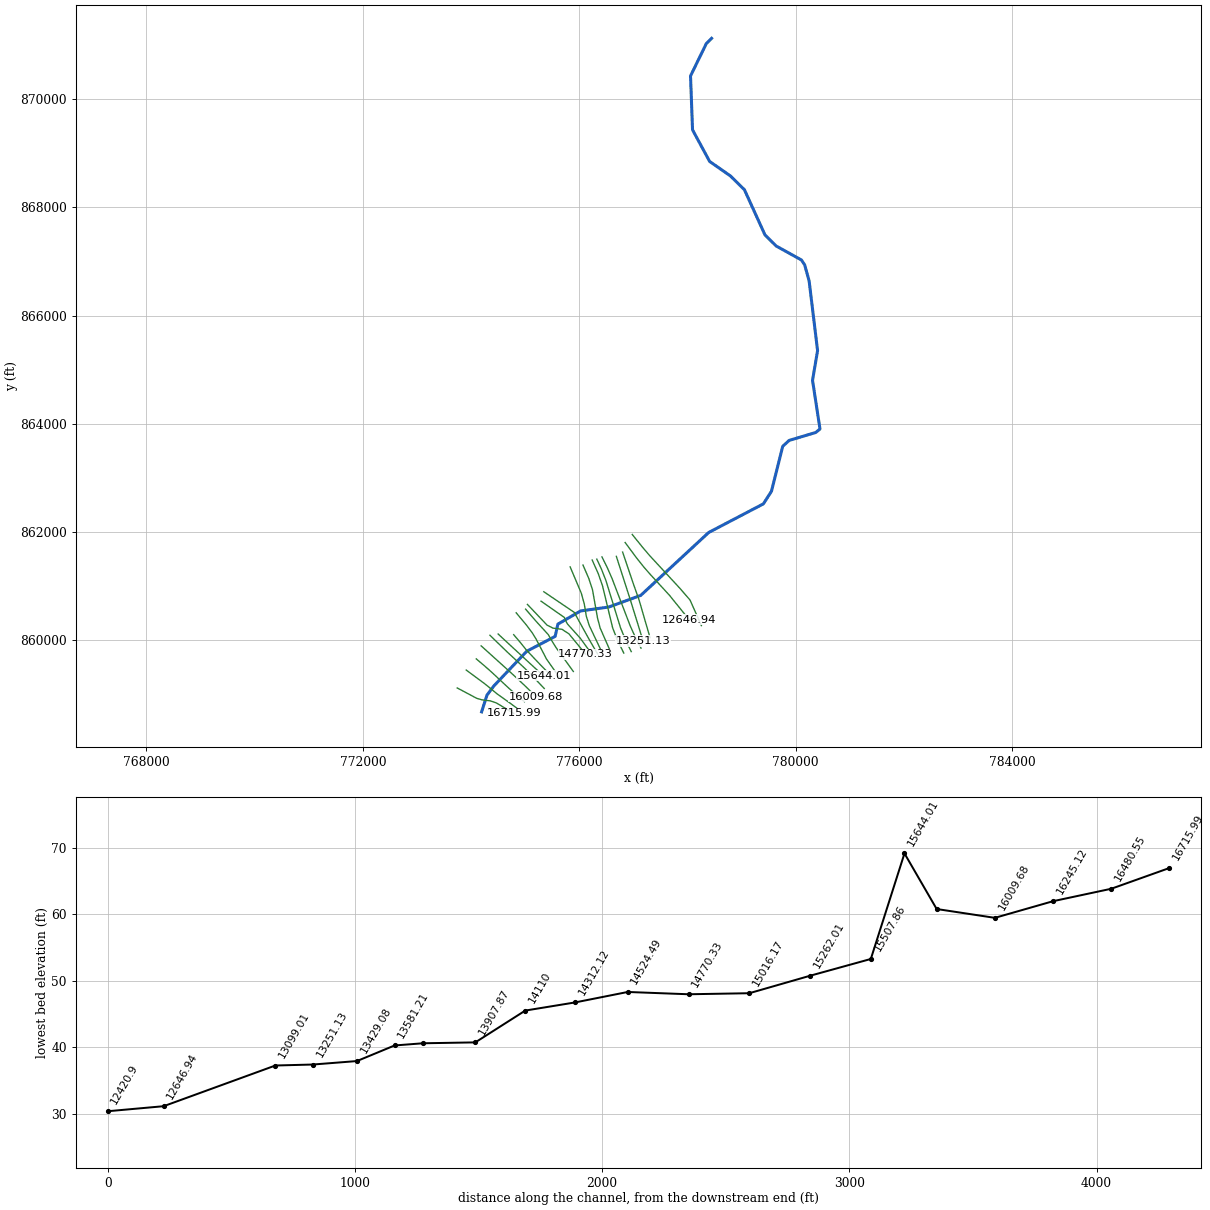
--- 16016_ras.prj (project) ---

Proj Title=16016
Current Plan=p01
Default Exp/Contr=0.3,0.1
English Units
Geom File=g01
Flow File=f01
Plan File=p01
Y Axis Title=Elevation
X Axis Title(PF)=Main Channel Distance
X Axis Title(XS)=Station
BEGIN DESCRIPTION:
RFD model 16016 exported to HEC-RAS
END DESCRIPTION:

--- 16016_ras.p01 (plan) ---

Plan Title=Plan 01
Program Version=4.10
Short Identifier=Plan 01
Geom File=g01
Flow File=f01
Subcritical Flow
Calc Critical at every XS
Secant Critical Depth

--- 16016_ras.f01 (steady flow) ---

Flow Title=Flow 01
Program Version=5.01
Number of Profiles= 6
Profile Names=10yr,25yr,50yr,100yr,100plus,500yr
River Rch & RM=16016,53,16715.99
  704.49 1142.85  1558.7  1941.7 2834.88 4068.61
River Rch & RM=16016,53,16480.55
  708.81  1149.9 1568.36 1953.76 2852.49 4090.43
River Rch & RM=16016,53,16245.12
   728.2  1181.6 1611.85 2008.13 2931.87 4188.79
River Rch & RM=16016,53,16009.68
  866.82 1407.56 1921.32 2394.42 3495.85 4874.34
River Rch & RM=16016,53,15774.25
  885.34 1437.89 1962.98 2446.57 3571.99 4966.24
River Rch & RM=16016,53,15644.01
  892.15 1449.03 1978.27  2465.7 3599.92 4999.86
River Rch & RM=16016,53,15507.86
  916.84 1489.56 2034.03 2535.57 3701.93 5122.83
River Rch & RM=16016,53,15262.01
  920.62 1495.75 2042.53 2546.21 3717.46 5141.44
River Rch & RM=16016,53,15016.17
  921.42 1497.07 2044.35 2548.48 3720.78 5145.42
River Rch & RM=16016,53,14770.33
  927.07 1506.32 2057.06  2564.4 3744.02 5173.28
River Rch & RM=16016,53,14524.49
 1091.74 1776.58 2428.91 3030.35  4424.3 5980.17
River Rch & RM=16016,53,14312.12
  1099.4 1789.19  2446.3 3052.17 4456.17 6017.68
River Rch & RM=16016,53,   14110
 1101.43 1792.55 2450.92 3057.98 4464.65 6027.67
River Rch & RM=16016,53,13907.87
 1111.85 1809.72  2474.6 3087.72 4508.07 6078.75
River Rch & RM=16016,53,13695.86
 1200.03 1955.11 2675.26  3339.8  4876.1 6509.42
River Rch & RM=16016,53,13581.21
 1201.78 1957.99 2679.23 3344.79 4883.39 6517.89
River Rch & RM=16016,53,13429.08
 1208.27 1968.67 2693.98 3363.31 4910.43 6549.33
River Rch & RM=16016,53,13251.13
 1209.76 1971.14 2697.38 3367.58 4916.67 6556.57
River Rch & RM=16016,53,13099.01
 1213.75 1977.71 2706.45 3378.97 4933.29 6575.88
River Rch & RM=16016,53,12646.94
  1218.7 1985.88 2717.74 3393.16 4954.02 6599.98
River Rch & RM=16016,53, 12420.9
 1242.44 2025.16 2772.08 3461.57  5053.9  6716.4
River Rch & RM=16016,53,12194.87
 1244.63  2028.8 2777.11 3467.91 5063.15 6727.16
River Rch & RM=16016,53,11968.83
 1246.58 2032.02 2781.57 3473.53 5071.35 6736.71
River Rch & RM=16016,53, 11742.8
 1250.71 2038.86 2791.04 3485.46 5088.77 6757.01
River Rch & RM=16016,53,11516.76
 1280.07 2087.59 2858.59 3570.64 5213.13 6901.97
River Rch & RM=16016,53,11149.34
 1285.13 2095.99 2870.22 3585.29 5234.52  6926.8
River Rch & RM=16016,53,10908.26
 1287.54 2099.99 2875.75 3592.26 5244.71 6938.62
River Rch & RM=16016,53,10667.18
 1608.75 2634.36 3617.64 4529.03 6612.39 8506.26
River Rch & RM=16016,53,10526.94
 1610.34    2637 3621.31 4533.67 6619.15 8513.89
River Rch & RM=16016,53,10213.26
  1615.1 2644.92 3632.31 4547.56 6639.43 8536.76
River Rch & RM=16016,53,10023.56
 1616.91 2647.93  3636.5 4552.85 6647.16 8545.46
River Rch & RM=16016,53,9587.377
 1619.61 2652.44 3642.76 4560.76 6658.71 8558.52
River Rch & RM=16016,53,9369.288
 1623.42  2658.8  3651.6 4571.95 6675.05 8576.99
River Rch & RM=16016,53,8496.932
 2844.18 4680.85 6452.36 8098.6811824.0714083.27
River Rch & RM=16016,53,8360.789
  2848.7 4688.43 6462.95 8112.1111843.6814103.83
River Rch & RM=16016,53,8008.269
 2858.71 4705.22  6486.4 8141.8611887.1114149.38
River Rch & RM=16016,53,7674.596
 2864.97 4715.73 6501.09  8160.511914.3214177.93
River Rch & RM=16016,53,7454.252
 2868.49 4721.64 6509.35 8170.9711929.6214193.98
River Rch & RM=16016,53,7205.904
 2870.83 4725.58 6514.85 8177.9511939.8114204.68
River Rch & RM=16016,53,6957.556
 2888.51 4755.31 6556.44 8230.7712016.9214285.69
River Rch & RM=16016,53,6709.207
  2892.6 4762.17 6566.04 8242.9512034.7114304.35
River Rch & RM=16016,53,6460.859
 2926.89 4819.84 6646.72 8345.4312184.3214461.33
River Rch & RM=16016,53,6212.511
 2928.82 4823.09 6651.26  8351.212192.7514470.18
River Rch & RM=16016,53,5964.162
 2930.74 4826.33  6655.8 8356.9712201.1714479.02
River Rch & RM=16016,53,5715.814
 2932.67 4829.57 6660.33 8362.7312209.5914487.87
River Rch & RM=16016,53,5467.465
 2935.17 4833.78 6666.23 8370.2312220.5414499.36
Boundary for River Rch & Prof#=16016,53,1
Up Type= 0
Dn Type= 2
Boundary for River Rch & Prof#=16016,53,2
Up Type= 0
Dn Type= 2
Boundary for River Rch & Prof#=16016,53,2
Up Type= 0
Dn Type= 2
Boundary for River Rch & Prof#=16016,53,2
Up Type= 0
Dn Type= 2
Boundary for River Rch & Prof#=16016,53,2
Up Type= 0
Dn Type= 2
Boundary for River Rch & Prof#=16016,53,2
Up Type= 0
Dn Type= 2

--- 16016_ras.g01 (geometry) ---

Geom Title=16016
Program Version=4.10

River Reach=16016,53
Reach XY= 30
774195.115463881858677.436654322774294.134637472858986.971781868
 774422.88677013859158.132402117775028.149585723859796.741604936
775553.862700189  860072.1622593775604.837833554860299.222784695
 776023.62832594860542.019641202776545.818520308860615.148768193
777136.030335781860830.122601424778391.407847263861992.389621606
 779402.37775066862521.397119921779551.295108557862753.864358415
779759.864555771863584.768887705779878.016974388863693.832658761
 780370.55593797863840.858873534780448.366546627 863905.59673502
780311.028374197864804.639997274780403.907195297 865353.73103059
780247.621976313866643.098801019 780165.14947575866939.053081382
780105.253642443867029.330859201779639.010109514867286.740146522
779431.141120551 867493.88529406779052.221467259868326.870733673
778794.607540459868580.983687575778409.316094248868849.718200412
778093.100864675869433.844748058778055.774475785870429.504470291
778348.220297724871028.985243668778445.606742174871125.065622345

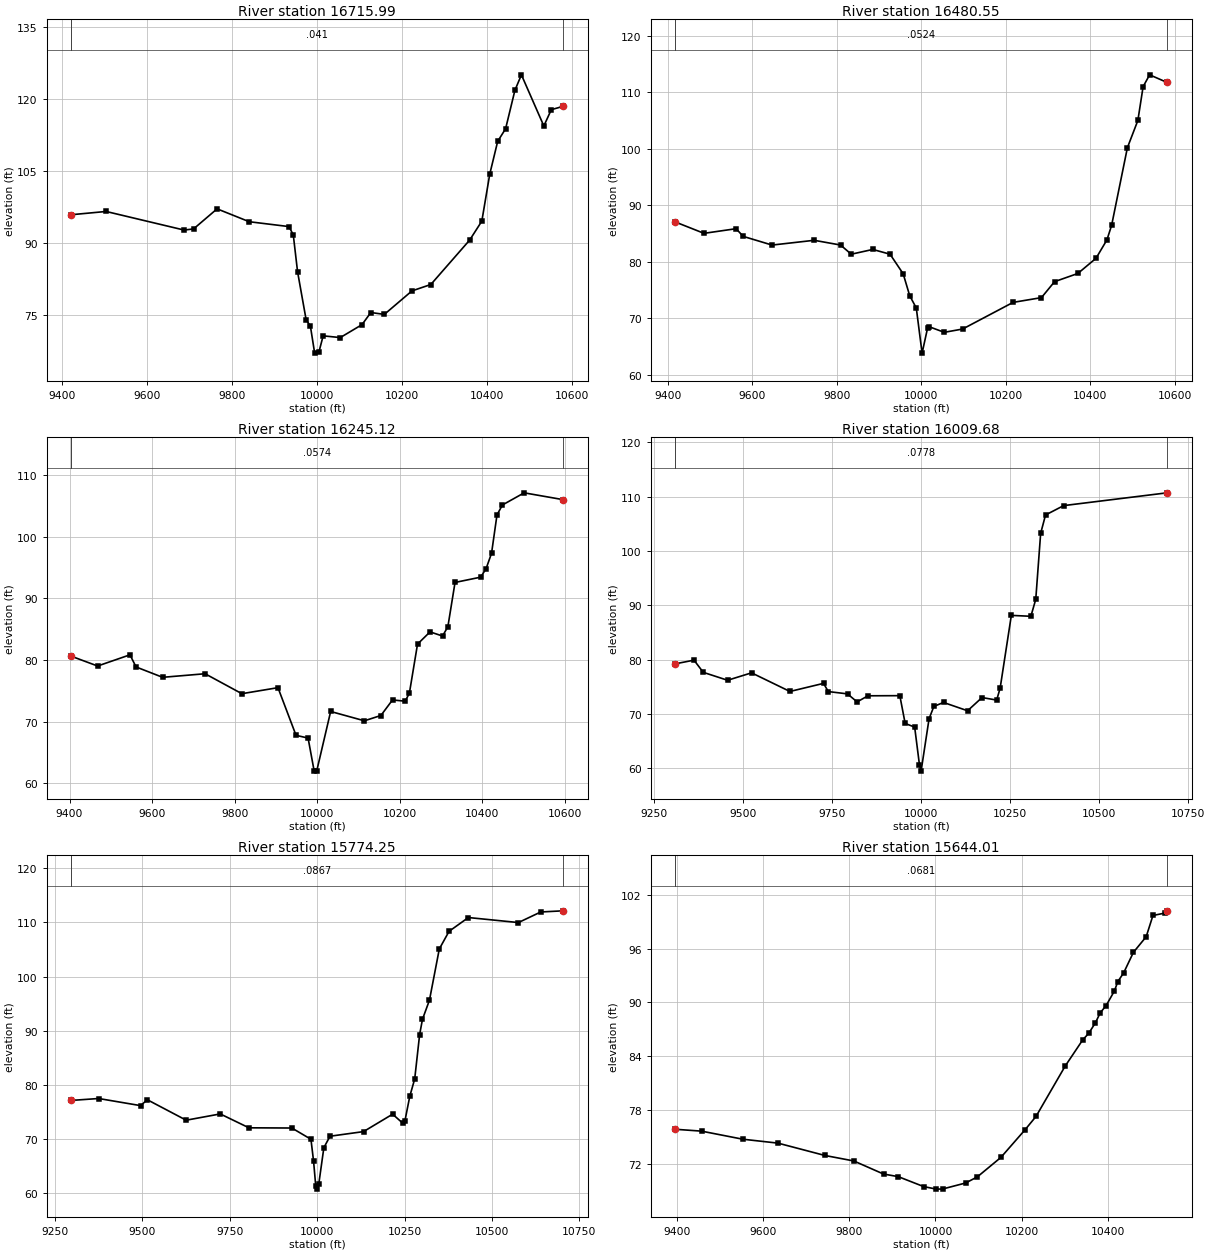
Type RM Length L Ch R = 1 ,16715.99,235.435700,235.435700,235.435700
XS GIS Cut Line= 6
773744.674992244 859119.13885499774105.142129748858927.325210565
774204.949794519858898.512359182774357.783574553858880.294114922
774469.121613081858841.829081964774788.410376381 858649.43236039
#Sta/Elev= 30
9420.89495.829869502.94996.509089686.63992.635069708.96592.867049764.42897.05679
9840.16194.370369933.79993.356919943.89891.619239953.99683.932289974.172 73.9172
9984.19272.611159994.212 66.970910004.2367.1966410014.26  70.57610054.5470.21352
10105.7572.9111210126.5775.4418710158.3475.0442510223.4179.9461610267.8581.27801
10359.4590.5535710388.01  94.49710406.68104.300610425.35 111.13310444.01113.7579
10465.94121.775310481.25125.001310534.07114.336910551.67117.740210579.08118.4138
#Mann= 3 , 0 , 0
9420.894   0.041       09420.894   0.041       010579.08   0.041       0
#XS Ineff= 2 , 0
       0                               0
Bank Sta=9420.894,10579.08
Exp/Cntr=0.3,0.1

Type RM Length L Ch R = 1 ,16480.55,235.435800,235.435800,235.435800
XS GIS Cut Line= 6
773910.237307767859450.061290813774234.568261041859210.378342763
774313.163145635859148.192386834774482.503277672 859008.44186577
774724.871372365858835.874367687774840.561739621858750.539286176
#Sta/Elev= 30
9417.80187.060499485.70785.052299561.657 85.87199578.56984.511629646.90682.97511
9746.60183.819539809.127 82.98129834.39481.35683  9885.482.199929926.27281.35767
9957.34377.892159972.87974.000659988.41571.8338710002.1563.8493110015.2868.34302
10019.3268.5099310054.6767.5324810098.0968.1123210217.6272.8314810284.7673.67227
10315.8376.4984610370.9777.9456710414.0380.63703 10439.983.9003710451.0186.47956
10488.29100.199610513.14 105.03910525.57111.019910540.98113.107510582.18111.7654
#Mann= 3 , 0 , 0
9417.801  0.0524       09417.801  0.0524       010582.18  0.0524       0
#XS Ineff= 2 , 0
       0                               0
Bank Sta=9417.801,10582.18
Exp/Cntr=0.3,0.1

Type RM Length L Ch R = 1 ,16245.12,235.435700,235.435700,235.435700
XS GIS Cut Line= 6
 774096.19699134859656.213135562774232.349268699859541.348437333
774327.859436008859458.075920802774406.411281878859386.662769004
774706.964962437859106.231598102 774986.35612943858864.528991526
#Sta/Elev= 30
9404.24380.626479468.09479.036959546.59480.854429561.20578.884759625.69477.20264
9728.52977.782879817.67774.546029905.18775.522779948.94367.78867 9978.1667.34782
9992.69862.06512    999961.9809210032.8471.6596110114.6170.1478210154.5471.00639
10182.7573.5303610213.4173.3297410223.6474.6316910243.34 82.585710273.6584.57439
10303.9583.9035710316.8785.4022810334.2692.5972510396.39  93.45410409.5694.83944
10422.7497.3331310435.91103.550410449.08105.166610501.77107.138210595.76 106.036
#Mann= 3 , 0 , 0
9404.243  0.0574       09404.243  0.0574       010595.76  0.0574       0
#XS Ineff= 2 , 0
       09872.409                       0
Bank Sta=9404.243,10595.76
Exp/Cntr=0.3,0.1

Type RM Length L Ch R = 1 ,16009.68,235.435700,235.435700,235.435700
XS GIS Cut Line= 6
774186.093418215859897.559321918774697.847069829859435.495553151
774699.335332778859434.159486762774824.589632508859320.274863646
774992.112497504859162.850490714775200.613988881858960.838944025
#Sta/Elev= 30
9309.51179.22969 9361.9379.90426 9387.9477.659959456.24276.202529523.60777.56827
9631.39274.140379725.70375.629849739.17674.118849793.06873.697059820.01472.21652
 9850.5273.343899940.05273.367849954.97468.253879981.691 67.58239995.16460.63196
9999.74259.4791910022.1769.1289910035.69 71.391210062.7272.11924 10130.370.58836
10170.8573.0199510212.0272.55775 10221.874.7646310253.1988.1414210308.0887.97499
 10321.891.0973710335.52103.224510349.24106.617110400.17108.344610690.48110.6969
#Mann= 3 , 0 , 0
9309.511  0.0778       09309.511  0.0778       010690.48  0.0778       0
#XS Ineff= 2 , 0
       09880.696        10171.99       0
Bank Sta=9309.511,10690.48
Exp/Cntr=0.3,0.1

Type RM Length L Ch R = 1 ,15774.25,130.236100,130.236100,130.236100
XS GIS Cut Line= 6
774348.673429072860092.854982977774664.362842996859787.603789655
774935.711230737859535.984076651775007.837098937 859467.11875896
775118.981850259859354.763271141775352.777960223859109.014956599
#Sta/Elev= 30
9296.92577.166199375.27677.519549495.242 76.20679514.37977.295319625.66273.51776
9723.03474.67619 9805.1172.114619927.83972.076049982.38570.003419989.93165.95133
9996.02261.45933   1000160.8047210004.6361.6783310019.3468.4512510036.9470.56312
10132.7871.4147310216.0274.6305810244.46  72.99110251.0273.3527510265.0877.93607
10279.15 81.135310293.2189.3211710301.34 92.128410321.3595.6641710349.48105.1031
10377.35 108.35710432.56110.900510575.72109.9741 10639.6111.925810703.07112.1379
#Mann= 3 , 0 , 0
9296.925  0.0867       09296.925  0.0867       010703.07  0.0867       0
#XS Ineff= 2 , 0
       09902.804        10136.26       0
Bank Sta=9296.925,10703.07
Exp/Cntr=0.3,0.1

Type RM Length L Ch R = 1 ,15644.01,136.153800,136.153800,136.153800
XS GIS Cut Line= 3
774500.033752978860116.253308952775082.273778588859577.989116102
775339.092641801859342.278652564
#Sta/Elev= 30
9396.04675.838069456.81775.631329552.61474.731129634.32574.292599743.27372.91654
9810.36572.304239879.45970.843939913.48370.556269972.40869.4490210002.0369.16193
 10016.6 69.177610070.1269.8477410097.3670.5353810151.8372.6984210208.18 75.7972
10233.3977.2709410301.2682.8994110341.9885.8192710355.55 86.532210370.8687.67973
 10382.788.8438210396.2789.6439610415.2391.2539510423.4292.3197710436.9993.29691
10459.5995.5819510489.1797.3169110504.8699.6887710532.0199.9498310537.56100.2069
#Mann= 3 , 0 , 0
9396.046  0.0681       09396.046  0.0681       010537.56  0.0681       0
#XS Ineff= 2 , 0
       09927.433         10119.6       0
Bank Sta=9396.046,10537.56
Exp/Cntr=0.3,0.1

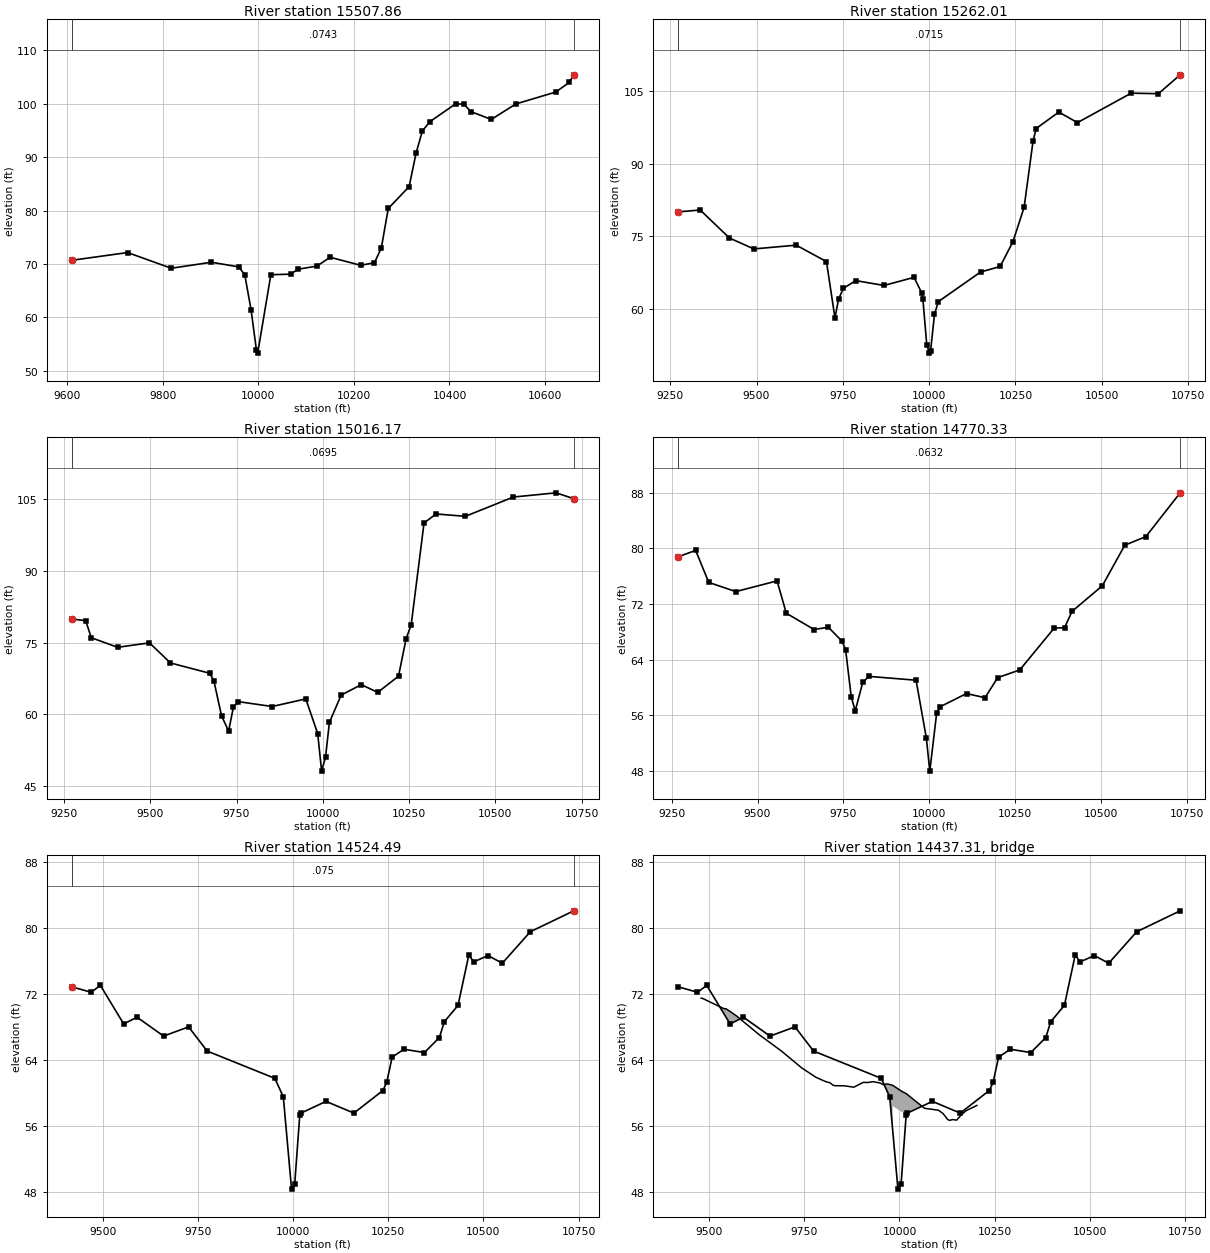
Type RM Length L Ch R = 1 ,15507.86,245.842200,245.842200,245.842200
XS GIS Cut Line= 5
774787.861877808860104.049586504774910.929170281859959.468260899
775022.759725392859819.855071977775272.249376029859556.880716383
775495.646606416859328.206386104
#Sta/Elev= 30
9609.29570.690599726.236 72.13879817.69969.200299901.64670.325659958.63669.45719
9971.44967.997139984.73361.360839995.82553.900789998.51753.2979610026.0967.98904
10067.4468.09019   1008369.0198110122.5869.6030810150.1471.2575210213.7769.75809
10242.8270.2156810257.35  72.99910271.8880.4021510315.4784.48441   1033090.72989
10343.1694.8946910358.7896.6518110413.06100.010710430.3399.9245110444.6498.55839
10487.5797.0775710538.88 99.980810622.76102.217610650.72 104.01510660.22105.4377
#Mann= 3 , 0 , 0
9609.295  0.0743       09609.295  0.0743       010660.22  0.0743       0
#XS Ineff= 2 , 0
       0                               0
Bank Sta=9609.295,10660.22
Exp/Cntr=0.3,0.1

Type RM Length L Ch R = 1 ,15262.01,245.842200,245.842200,245.842200
XS GIS Cut Line= 6
774833.573117859860508.130071067775023.751701788860281.228483822
775133.136131151860134.956116341775206.946084702860013.559647663
775394.708136072859652.661393217 775640.29914601859304.657250121
#Sta/Elev= 30
9273.01479.999849336.905 80.38189421.61474.58695  9492.372.332269614.91973.11167
9702.56969.705269727.14358.068949737.76661.978749751.71664.187939787.35565.77636
9869.22564.778049956.207 66.44649978.41963.232719981.87361.900389993.072  52.504
10000.68 50.776310004.2451.3086710015.3758.7681510026.4961.4276410148.9267.55642
10205.67  68.70310242.5173.8087210274.9480.9115610300.8994.62873   1031097.24632
 10375.4100.643810429.4998.4624410585.13104.556210663.99104.4467   10727108.3514
#Mann= 3 , 0 , 0
9273.014  0.0715       09273.014  0.0715       0   10727  0.0715       0
#XS Ineff= 2 , 0
       09909.076                       0
Bank Sta=9273.014,10727
Exp/Cntr=0.3,0.1

Type RM Length L Ch R = 1 ,15016.17,245.842300,245.842300,245.842300
XS GIS Cut Line= 6
775008.013141369860575.474163684775197.462795188860356.180139789
775427.528363925860104.339629825  775523.4259062859939.528649041
775580.312518843859851.927827843775890.334827114859423.617626184
#Sta/Elev= 30
9272.51379.893829312.78479.573569329.091 75.99959405.57473.996749497.79374.92842
9558.54170.727879672.25468.585589684.41767.008689706.50759.712619727.13156.50586
9740.90161.479519754.67162.660199853.30861.642579950.82563.224079985.331 55.9904
 9996.6948.1522710007.9651.0596210019.2458.3191710053.3764.0254210111.6666.20227
10159.3664.5925210219.5267.9681810241.5775.7875210256.2578.6735510293.5599.95937
10328.21 101.83110413.45101.342110552.42105.366510676.29106.244710727.54105.0134
#Mann= 3 , 0 , 0
9272.513  0.0695       09272.513  0.0695       010727.54  0.0695       0
#XS Ineff= 2 , 0
       09921.894                       0
Bank Sta=9272.513,10727.54
Exp/Cntr=0.3,0.1

Type RM Length L Ch R = 1 ,14770.33,245.842200,245.842200,245.842200
XS GIS Cut Line= 6
775042.003495697860662.879904821 775404.67420326860280.332792056
775513.890682601860224.907810864775679.409567986860203.692475804
775808.742312442 860119.11788145776118.228993278859743.174536844
#Sta/Elev= 30
9268.75378.77781 9319.7179.69545 9357.8375.102429436.56773.77864 9556.8875.31666
9583.81370.668879664.84368.331489706.36968.661249746.296 66.64659756.72265.39671
9773.022 58.62819784.73856.676269806.51860.750149824.413 61.60359961.80561.05072
 9991.8252.7511410001.8247.9956710021.8456.3399510031.8557.2363210108.8259.14086
10162.6958.5351410199.5561.4179210263.9862.5305710364.1668.5333410394.4368.59322
10416.3270.9431710504.4874.6156610569.9280.4424110631.2681.6757510731.2387.96366
#Mann= 3 , 0 , 0
9268.753  0.0632       09268.753  0.0632       010731.23  0.0632       0
#XS Ineff= 2 , 0
       0 9935.45        10135.28       0
Bank Sta=9268.753,10731.23
Exp/Cntr=0.3,0.1

Type RM Length L Ch R = 1 ,14524.49,212.370000,212.370000,212.370000
XS GIS Cut Line= 6
775293.357775748 860723.11980091775723.940549195860422.536025599
775761.480136871860336.481529519775784.946248412860297.579202384
 776019.24655962 860037.68096064776197.406902492859791.304754928
#Sta/Elev= 30
9418.62172.855299469.40672.190529493.79773.021059555.09668.350759590.03669.16957
9659.91666.880229725.51367.997899774.29565.067719952.11261.763819974.32759.51321
9995.93648.3394110004.1948.9141810017.5657.3223710021.0457.5552510086.4758.97183
10159.7657.5490310235.8160.28763 10245.961.2662310260.2664.3325910291.1665.28772
   1034564.8864210384.3166.7077210397.4168.6339510433.2170.5936210461.6976.72511
10474.2675.8662410511.9476.6384910549.6275.7111410623.1979.5256610737.3282.05806
#Mann= 3 , 0 , 0
9418.621   0.075       09418.621   0.075       010737.32   0.075       0
#XS Ineff= 2 , 0
       0                10082.21       0
Bank Sta=9418.621,10737.32
Exp/Cntr=0.3,0.1

Type RM Length L Ch R = 3 ,14437.31,,,
BEGIN DESCRIPTION:
END DESCRIPTION:
Bridge Culvert--1,0,-1,-1, 0
Deck Dist Width WeirC Skew NumUp NumDn MinLoCord MaxHiCord MaxSubmerge Is_Ogee
86.985000,38.400000,2.6,0, 37, 37, , , 0.95, 0, 0,0,,
 9479.08 9482.04 9538.66 9544.20 9555.49 9572.32 9631.23 9690.14 9743.12 9780.42
 9805.28 9817.72 9824.78 9830.15 9855.01 9879.88 9904.74 9917.18 9929.61 9949.27
 9956.60 9968.76 9982.10 9982.1010005.2210017.9010017.9010065.9910102.4610114.61
10126.7710132.5610138.9210150.1510163.2310175.3810203.36
   71.47   71.46   70.21   70.19   69.85   69.31   67.06   65.06   63.03   61.89
   61.38   61.22   60.95   60.87   60.86   60.69   61.27   61.26   61.36   61.20
   61.01   61.08   60.92   60.92   60.21   59.90   59.90   58.13   57.90   57.49
   56.76   56.67   56.77   56.70   57.39   57.85   58.48
 -928.53 -928.54 -929.79 -929.81 -930.15 -930.69 -932.94 -934.94 -936.97 -938.11
 -938.62 -938.78 -939.05 -939.13 -939.14 -939.31 -938.73 -938.74 -938.64 -938.80
 -938.99 -938.92 -939.08   58.42   57.71   57.40 -940.10 -941.87 -942.10 -942.51
 -943.24 -943.33 -943.23 -943.30 -942.61 -942.15 -941.52
 9479.08 9482.04 9538.66 9544.20 9555.49 9572.32 9631.23 9690.14 9743.12 9780.42
 9805.28 9817.72 9824.78 9830.15 9855.01 9879.88 9904.74 9917.18 9929.61 9949.27
 9956.60 9968.76 9982.10 9982.1010005.2210017.9010017.9010065.9910102.4610114.61
10126.7710132.5610138.9210150.1510163.2310175.3810203.36
   71.47   71.46   70.21   70.19   69.85   69.31   67.06   65.06   63.03   61.89
   61.38   61.22   60.95   60.87   60.86   60.69   61.27   61.26   61.36   61.20
   61.01   61.08   60.92   60.92   60.21   59.90   59.90   58.13   57.90   57.49
   56.76   56.67   56.77   56.70   57.39   57.85   58.48
 -928.53 -928.54 -929.79 -929.81 -930.15 -930.69 -932.94 -934.94 -936.97 -938.11
 -938.62 -938.78 -939.05 -939.13 -939.14 -939.31 -938.73 -938.74 -938.64 -938.80
 -938.99 -938.92 -939.08   58.42   57.71   57.40 -940.10 -941.87 -942.10 -942.51
 -943.24 -943.33 -943.23 -943.30 -942.61 -942.15 -941.52
BR Coef=-1 , 0 , 0 ,, 0 ,,,0.8,0,1,0,
WSPro=,,,, 1 ,,,, 0 ,,,, 0 ,,,,-1 ,-1 ,-1 , 0 , 0 , 0 , 0 , 0
BC Design=,, 0 ,, 0 ,,,,,,

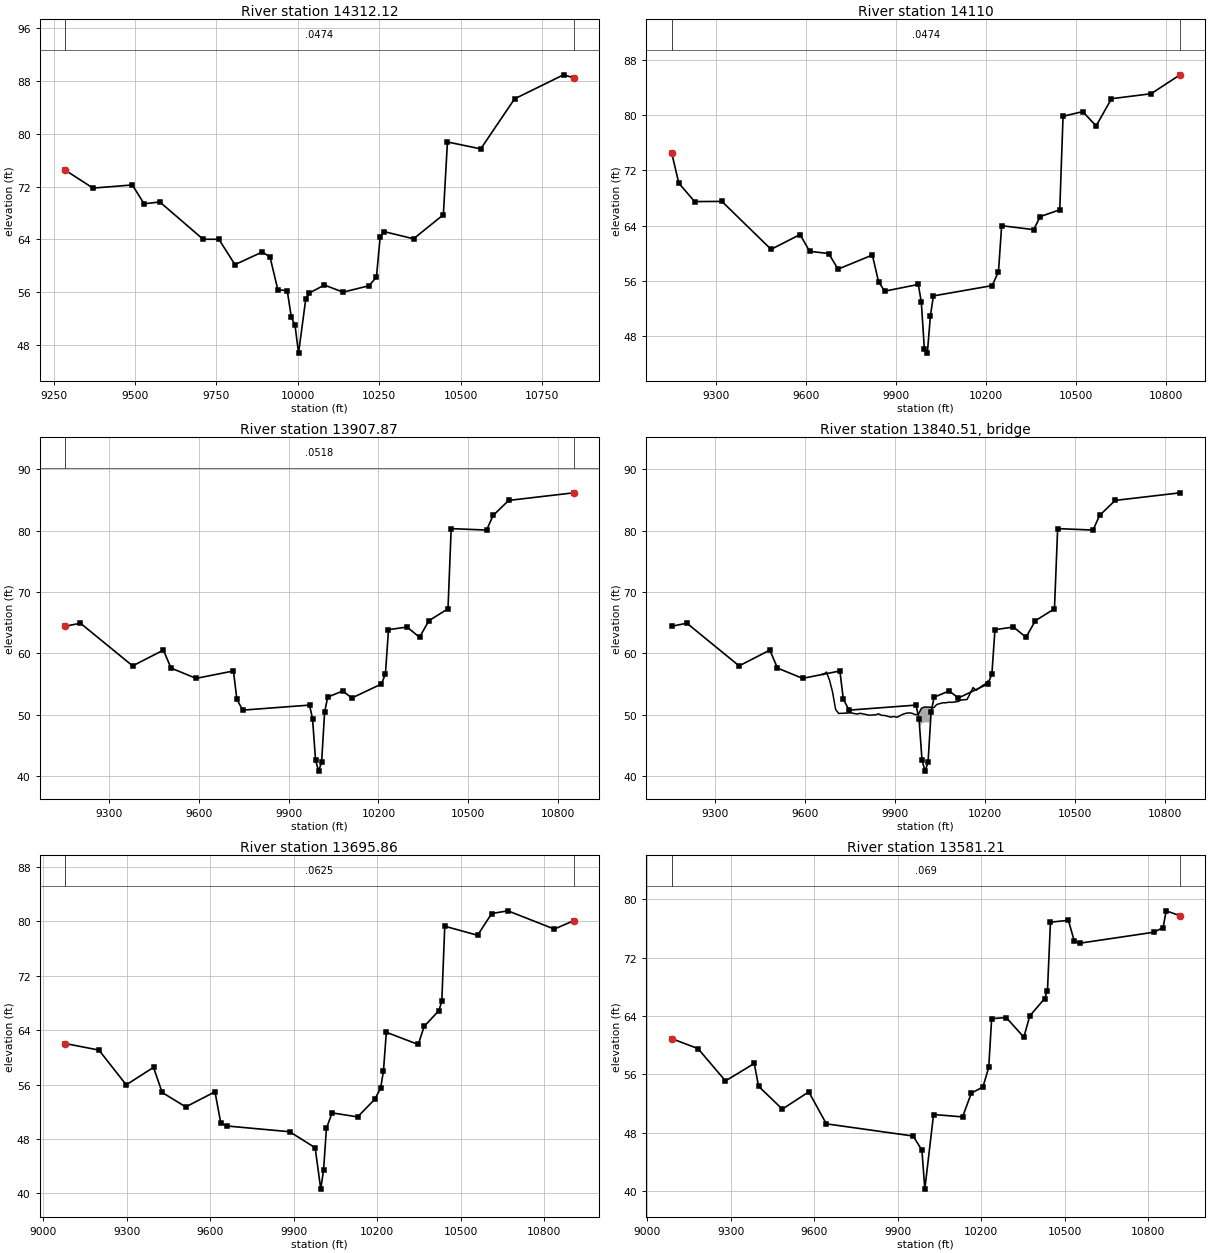
Type RM Length L Ch R = 1 ,14312.12,202.122400,202.122400,202.122400
XS GIS Cut Line= 6
775344.369741768 860897.26409857 775912.30431512860512.764908955
775936.949476719860461.061536208776098.010190219860167.919044659
776204.960669994859977.114838421776338.017417639859748.435905963
#Sta/Elev= 30
9285.478  74.4829370.77371.766869491.53572.242999527.76369.394259576.06869.66367
9708.90764.015619757.21164.017729806.80460.17676 9890.0562.074329914.20261.36874
9938.35456.382919967.34156.22181 9979.93 52.17029991.00851.0430110002.0246.77165
10024.1354.9627310035.5655.8916610081.4257.0814310138.7456.00777 10218.556.97849
10241.2658.3038210252.6464.3916210264.01 65.185710355.0464.0867610446.6867.72869
 10459.278.7520410561.4577.7054810665.2685.2820510815.6688.92234 10846.488.48161
#Mann= 3 , 0 , 0
9285.478  0.0474       09285.478  0.0474       0 10846.4  0.0474       0
#XS Ineff= 2 , 0
       0                 10091.1       0
Bank Sta=9285.478,10846.4
Exp/Cntr=0.3,0.1

Type RM Length L Ch R = 1 ,   14110,202.122500,202.122500,202.122500
XS GIS Cut Line= 6
775831.329335833861356.333520976776037.967634825860869.025842739
776092.082499801860672.471897594776129.836539237860445.233050918
776185.458784762860269.651754689776420.387651273859776.308557769
#Sta/Elev= 30
9152.30774.546379176.05770.144779228.93267.480119319.82767.504229483.89860.56382
9580.58362.715029612.33360.281449675.833 59.96059707.25657.701959821.63759.74275
9842.25155.874559862.865 54.51519974.87255.487279984.94152.92429 9995.0146.18245
10005.0845.5453710015.1550.9067310025.2353.8275210221.09 55.318210242.2657.31733
10252.8563.98926 10359.763.4180510381.2465.2987710446.6666.2956610457.6179.82609
10523.3780.5008510567.89 78.422310619.1882.3702910751.0983.0888810847.6985.82665
#Mann= 3 , 0 , 0
9152.307  0.0474       09152.307  0.0474       010847.69  0.0474       0
#XS Ineff= 2 , 0
       09821.052        10090.08       0
Bank Sta=9152.307,10847.69
Exp/Cntr=0.3,0.1

Type RM Length L Ch R = 1 ,13907.87,212.016700,212.016700,212.016700
XS GIS Cut Line= 6
776068.281037584861391.246281151776175.406276805861143.821681029
776243.931137504860936.275210446776336.654463192 860414.03553585
776385.682155999860226.871185096776580.458472662859783.250882415
#Sta/Elev= 30
9153.989  64.3979204.832 64.89079379.25757.930819481.86960.502769507.38357.57408
9591.32255.893679715.86757.100969727.28552.487659746.66350.713659969.939 51.5331
9980.02749.329969990.11442.58927 10000.240.7638710010.2942.2019810020.3850.36908
10030.4752.8230510080.9353.8469910111.3152.6899910210.1354.97894 10223.556.62315
10233.7663.8402610295.6664.2677910337.3962.5958810368.7265.3008810432.4967.24424
10443.1280.3212210561.3680.0855210583.0982.4640710635.1684.9208110851.76 86.1588
#Mann= 3 , 0 , 0
9153.989  0.0518       09153.989  0.0518       010851.76  0.0518       0
#XS Ineff= 2 , 0
       09794.136        10066.16       0
Bank Sta=9153.989,10851.76
Exp/Cntr=0.3,0.1

Type RM Length L Ch R = 3 ,13840.51,,,
BEGIN DESCRIPTION:
END DESCRIPTION:
Bridge Culvert--1,0,-1,-1, 0
Deck Dist Width WeirC Skew NumUp NumDn MinLoCord MaxHiCord MaxSubmerge Is_Ogee
86.808350,38.400000,2.6,0, 44, 44, , , 0.95, 0, 0,0,,
 9657.68 9660.55 9670.80 9681.05 9691.29 9701.54 9711.78 9752.77 9773.26 9783.51
 9814.25 9834.74 9844.98 9855.23 9865.48 9885.97 9896.21 9906.46 9926.95 9937.20
 9947.45 9957.69 9967.94 9978.18 9983.10 9983.10 9988.43 9998.6810016.9010016.90
10029.4010039.5010059.7210069.8310079.9310090.0410110.2610120.3710140.5810160.80
10170.9110191.1210201.2310210.11
   56.61   56.51   56.92   55.63   53.67   50.82   50.17   50.27   50.07   50.20
   49.88   49.95   50.11   49.86   49.84   49.57   49.67   49.55   50.06   50.21
   50.27   50.19   49.96   50.08   50.54   50.54   51.03   51.23   51.20   51.20
   51.10   51.64   51.91   51.91   52.01   51.98   52.12   52.36   52.45   54.40
   53.94   54.69   54.98   55.45
 -943.39 -943.49 -943.08 -944.37 -946.33 -949.18 -949.83 -949.73 -949.93 -949.80
 -950.12 -950.05 -949.89 -950.14 -950.16 -950.43 -950.33 -950.45 -949.94 -949.79
 -949.73 -949.81 -950.04 -949.92 -949.46   48.04   48.53   48.73   48.70 -948.80
 -948.90 -948.36 -948.09 -948.09 -947.99 -948.02 -947.88 -947.64 -947.55 -945.60
 -946.06 -945.31 -945.02 -944.55
 9657.68 9660.55 9670.80 9681.05 9691.29 9701.54 9711.78 9752.77 9773.26 9783.51
 9814.25 9834.74 9844.98 9855.23 9865.48 9885.97 9896.21 9906.46 9926.95 9937.20
 9947.45 9957.69 9967.94 9978.18 9983.10 9983.10 9988.43 9998.6810016.9010016.90
10029.4010039.5010059.7210069.8310079.9310090.0410110.2610120.3710140.5810160.80
10170.9110191.1210201.2310210.11
   56.61   56.51   56.92   55.63   53.67   50.82   50.17   50.27   50.07   50.20
   49.88   49.95   50.11   49.86   49.84   49.57   49.67   49.55   50.06   50.21
   50.27   50.19   49.96   50.08   50.54   50.54   51.03   51.23   51.20   51.20
   51.10   51.64   51.91   51.91   52.01   51.98   52.12   52.36   52.45   54.40
   53.94   54.69   54.98   55.45
 -943.39 -943.49 -943.08 -944.37 -946.33 -949.18 -949.83 -949.73 -949.93 -949.80
 -950.12 -950.05 -949.89 -950.14 -950.16 -950.43 -950.33 -950.45 -949.94 -949.79
 -949.73 -949.81 -950.04 -949.92 -949.46   48.04   48.53   48.73   48.70 -948.80
 -948.90 -948.36 -948.09 -948.09 -947.99 -948.02 -947.88 -947.64 -947.55 -945.60
 -946.06 -945.31 -945.02 -944.55
BR Coef=-1 , 0 , 0 ,, 0 ,,,0.8,0,1,0,
WSPro=,,,, 1 ,,,, 0 ,,,, 0 ,,,,-1 ,-1 ,-1 , 0 , 0 , 0 , 0 , 0
BC Design=,, 0 ,, 0 ,,,,,,

Type RM Length L Ch R = 1 ,13695.86,114.649000,114.649000,114.649000
XS GIS Cut Line= 6
776237.892095581861484.471889438776349.014272852861236.428417501
776428.944024776861009.129012255776615.945043242860232.087765059
776704.577436199860005.156156752776822.454526874859763.454064107
#Sta/Elev= 30
9079.13962.031669200.21961.070089298.26455.955299396.30558.530779427.33354.83569
9512.07952.714289617.06454.938149637.84750.33777 9658.6349.916469885.15549.06622
9976.70746.715669996.93940.6291610007.0743.48222 10017.2 49.545610037.4651.83594
10129.3451.2478810191.0253.8442610211.6955.4481110222.0257.9677410232.3663.68557
10347.1261.8932810368.0764.5416510420.9366.8585610431.5868.2362710442.2479.27738
10560.0577.9499110610.92 81.1454   1066981.5402510835.5878.8571210904.7180.07681
#Mann= 3 , 0 , 0
9079.139  0.0625       09079.139  0.0625       010904.71  0.0625       0
#XS Ineff= 2 , 0
       09767.427        10053.11       0
Bank Sta=9079.139,10904.71
Exp/Cntr=0.3,0.1

Type RM Length L Ch R = 1 ,13581.21,152.130500,152.130500,152.130500
XS GIS Cut Line= 6
776323.899615722861500.388364571776410.549373194861313.711413203
776492.069464886861104.941274734776762.787391269860229.439290429
776864.010162633859986.287919751776960.420980738859790.866360993
#Sta/Elev= 30
9087.22960.912789181.81159.547939280.71755.120019384.21757.507919399.67354.38703
9485.16551.255149580.27853.623259643.40949.241829955.68247.568919987.08545.62827
9997.55340.30008 10028.950.5206610133.3350.1924810164.6653.4444810206.4354.28542
10227.3456.9605210237.8463.6451510290.3763.8006810353.6661.1048510374.8764.02215
 10427.9  66.37310438.5867.4952310449.3376.8635910513.87 77.109710535.3874.21501
10556.8973.9947910820.7975.4826910854.2576.11478 10865.578.4149110915.1577.73876
#Mann= 3 , 0 , 0
9087.229   0.069       09087.229   0.069       010915.15   0.069       0
#XS Ineff= 2 , 0
       09769.628        10055.62       0
Bank Sta=9087.229,10915.15
Exp/Cntr=0.3,0.1

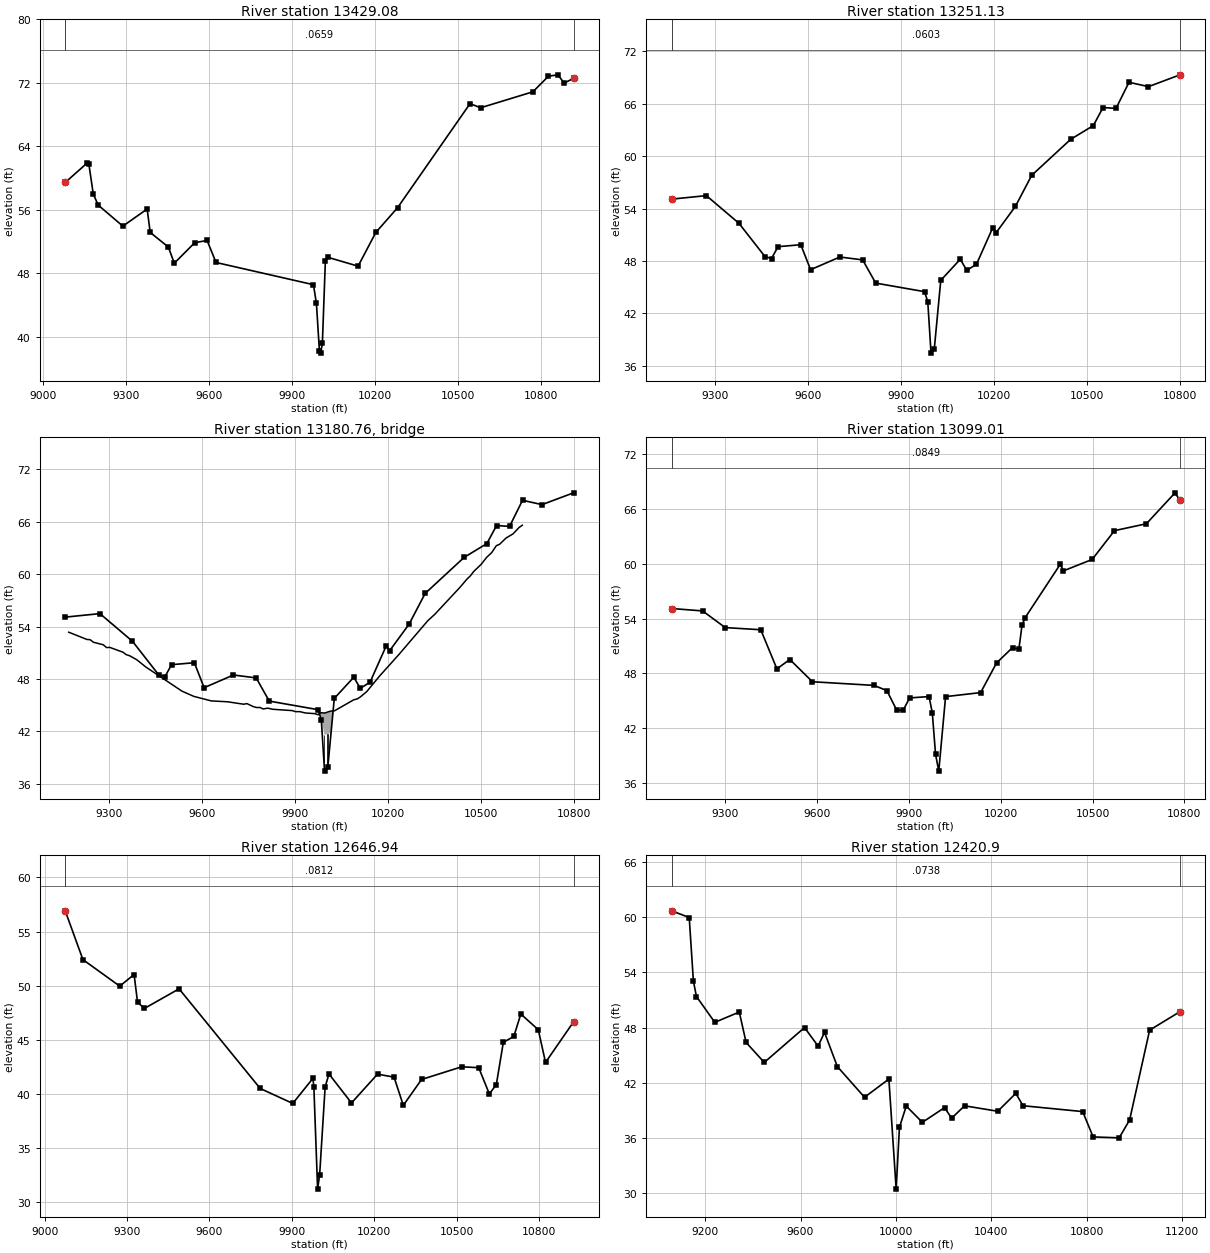
Type RM Length L Ch R = 1 ,13429.08,177.944600,177.944600,177.944600
XS GIS Cut Line= 6
776418.994431049861541.277566745776512.819253204861353.334427056
 776602.86031829861148.078476046776940.333322681860268.856653501
 777025.10200204860081.682354696777141.656242259859855.063691682
#Sta/Elev= 30
9081.78159.44474 9161.1361.895159167.37861.731649183.16857.986399201.04456.59304
9290.00853.949299377.852 56.0984 9388.8353.152369454.23951.321469475.94449.28158
  9549.651.858659594.38952.144539626.56449.371039978.56946.573359989.34844.21404
10000.1338.2542210004.7337.9576810010.9139.23031 10021.749.6107710031.38 50.0174
10139.8448.90489   1020453.1570210282.5756.2687710544.3469.3722210582.4968.85037
 10771.470.8602810827.66 72.827310861.6572.9989710884.3171.9633310918.2272.54824
#Mann= 3 , 0 , 0
9081.781  0.0659       09081.781  0.0659       010918.22  0.0659       0
#XS Ineff= 2 , 0
       09783.291        10069.98       0
Bank Sta=9081.781,10918.22
Exp/Cntr=0.3,0.1

Type RM Length L Ch R = 1 ,13251.13,152.119600,152.119600,152.119600
XS GIS Cut Line= 6
776684.753123939861551.624489889776928.476585865860794.424712166
776946.179846257860737.793606788776946.757713199 860735.87890844
776966.520021528860673.676934719777179.041484028859987.843877345
#Sta/Elev= 30
9159.64755.076159271.65855.477169376.71152.307799460.75348.490999481.76348.27422
9502.77449.629729576.31149.853549607.82646.992889702.37448.44776 9775.9148.11465
9817.93145.458179975.45644.476589985.93343.33119 9996.41 37.436910006.89 37.8975
10027.8545.7715310090.79  48.19110111.7346.9209110143.1347.6180910195.4851.79332
10205.9551.2066310268.76 54.249210321.1157.7964310446.7461.9176810520.0263.49841
10551.4365.56926 10593.365.4669610635.1868.45913   10698 67.961810799.7169.31364
#Mann= 3 , 0 , 0
9159.647  0.0603       09159.647  0.0603       010799.71  0.0603       0
#XS Ineff= 2 , 0
       09796.114        10072.23       0
Bank Sta=9159.647,10799.71
Exp/Cntr=0.3,0.1

Type RM Length L Ch R = 3 ,13180.76,,,
BEGIN DESCRIPTION:
END DESCRIPTION:
Bridge Culvert--1,0,-1,-1, 0
Deck Dist Width WeirC Skew NumUp NumDn MinLoCord MaxHiCord MaxSubmerge Is_Ogee
50.809800,50.500000,2.6,0, 57, 57, , , 0.95, 0, 0,0,,
 9171.03 9229.52 9240.10 9250.68 9282.41 9292.99 9303.56 9345.87 9356.45 9367.03
 9390.37 9419.92 9536.27 9574.47 9630.96 9683.22 9735.48 9745.93 9766.83 9777.28
 9787.74 9798.19 9813.45 9829.54 9892.25 9902.70 9916.63 9934.06 9965.41 9975.86
 9984.60 9984.60 9996.7710015.4010015.4010028.1210090.8310101.2810111.7310132.63
10174.4410237.1510329.3710352.1210432.5610456.6310467.0810477.5310501.3510519.34
10535.7410550.6910561.1510582.0510604.5310623.8510634.43
   53.35   52.52   52.49   52.20   51.91   51.59   51.61   51.06   50.78   50.66
   50.20   49.36   46.60   46.00   45.48   45.38   45.10   45.17   44.82   44.72
   44.73   44.56   44.65   44.52   44.37   44.25   44.25   44.10   44.02   43.89
   44.13   44.13   44.09   44.31   44.31   44.34   45.61   45.70   45.93   46.55
   48.35   50.83   54.66   55.40   58.46   59.46   59.81   60.30   61.11   61.92
   62.47   63.26   63.42   64.14   64.61   65.34   65.60
 -946.65 -947.48 -947.51 -947.80 -948.09 -948.41 -948.39 -948.94 -949.22 -949.34
 -949.80 -950.64 -953.40 -954.00 -954.52 -954.62 -954.90 -954.83 -955.18 -955.28
 -955.27 -955.44 -955.35 -955.48 -955.63 -955.75 -955.75 -955.90 -955.98 -956.11
 -955.87   41.63   41.59   41.81 -955.69 -955.66 -954.39 -954.30 -954.07 -953.45
 -951.65 -949.17 -945.34 -944.60 -941.54 -940.54 -940.19 -939.70 -938.89 -938.08
 -937.53 -936.74 -936.58 -935.86 -935.39 -934.66 -934.40
 9171.03 9229.52 9240.10 9250.68 9282.41 9292.99 9303.56 9345.87 9356.45 9367.03
 9390.37 9419.92 9536.27 9574.47 9630.96 9683.22 9735.48 9745.93 9766.83 9777.28
 9787.74 9798.19 9813.45 9829.54 9892.25 9902.70 9916.63 9934.06 9965.41 9975.86
 9984.60 9984.60 9996.7710015.4010015.4010028.1210090.8310101.2810111.7310132.63
10174.4410237.1510329.3710352.1210432.5610456.6310467.0810477.5310501.3510519.34
10535.7410550.6910561.1510582.0510604.5310623.8510634.43
   53.35   52.52   52.49   52.20   51.91   51.59   51.61   51.06   50.78   50.66
   50.20   49.36   46.60   46.00   45.48   45.38   45.10   45.17   44.82   44.72
   44.73   44.56   44.65   44.52   44.37   44.25   44.25   44.10   44.02   43.89
   44.13   44.13   44.09   44.31   44.31   44.34   45.61   45.70   45.93   46.55
   48.35   50.83   54.66   55.40   58.46   59.46   59.81   60.30   61.11   61.92
   62.47   63.26   63.42   64.14   64.61   65.34   65.60
 -946.65 -947.48 -947.51 -947.80 -948.09 -948.41 -948.39 -948.94 -949.22 -949.34
 -949.80 -950.64 -953.40 -954.00 -954.52 -954.62 -954.90 -954.83 -955.18 -955.28
 -955.27 -955.44 -955.35 -955.48 -955.63 -955.75 -955.75 -955.90 -955.98 -956.11
 -955.87   41.63   41.59   41.81 -955.69 -955.66 -954.39 -954.30 -954.07 -953.45
 -951.65 -949.17 -945.34 -944.60 -941.54 -940.54 -940.19 -939.70 -938.89 -938.08
 -937.53 -936.74 -936.58 -935.86 -935.39 -934.66 -934.40
Pier Skew, UpSta & Num, DnSta & Num=  ,9994.53, 2 ,9994.53, 2 , 0 , 0 , 0 ,,
    2.00    2.00
 -955.89   44.11
    2.00    2.00
 -955.89   44.11
Pier Skew, UpSta & Num, DnSta & Num=  ,10005.47, 2 ,10005.47, 2 , 0 , 0 , 0 ,,
    2.00    2.00
 -955.82   44.18
    2.00    2.00
 -955.82   44.18
BR Coef=-1 , 0 , 0 ,, 0 ,,,0.8,0,1,0,
WSPro=,,,, 1 ,,,, 0 ,,,, 0 ,,,,-1 ,-1 ,-1 , 0 , 0 , 0 , 0 , 0
BC Design=,, 0 ,, 0 ,,,,,,

Type RM Length L Ch R = 1 ,13099.01,452.071900,452.071900,452.071900
XS GIS Cut Line= 5
776800.849322379861630.780988827776996.102019817861053.818063155
777084.375174493860803.518089756 777091.48632592860791.222267583
777307.450915664860049.410043195
#Sta/Elev= 30
9124.131 55.09449225.24854.829569299.14853.006459415.27652.768899468.06148.48696
 9510.2949.51094 9584.1947.075639785.00246.676639827.41646.108999859.227 43.9879
9880.43543.930299901.64245.301939965.26445.453659975.86843.697469986.47139.14817
9997.07537.2889710019.3345.44751 10133.945.8871310185.9749.1369710238.0550.81008
10258.88 50.6456 10269.353.2919610279.7154.1074310394.2859.9467410404.6959.22071
10498.4360.4674410571.3363.6213810675.4964.3713710769.2267.7606810785.4666.92625
#Mann= 3 , 0 , 0
9124.131  0.0849       09124.131  0.0849       010785.46  0.0849       0
#XS Ineff= 2 , 0
       0 9799.56        10074.86       0
Bank Sta=9124.131,10785.46
Exp/Cntr=0.3,0.1

Type RM Length L Ch R = 1 ,12646.94,226.036000,226.036000,226.036000
XS GIS Cut Line= 6
776847.741000629861807.045156958777049.738988623861534.009624129
777187.624934279861360.621401647777303.407643071861227.198790376
777668.135709103860830.346336167778028.070979396860384.274602511
#Sta/Elev= 30
9074.94756.914219139.45252.40021 9273.4349.947389325.70551.023739338.22548.45733
9363.26647.885269489.33449.700179784.70140.482089903.07439.099329976.36841.41326
9979.91140.660469993.58831.17307   1000132.48843   1002140.6250910034.9141.82521
10116.9239.1435210211.6341.8098710271.84 41.529510305.4638.9225610371.9441.31541
10518.22 42.490310580.0342.4033510618.6439.97599 10644.140.8432910669.5544.75163
10707.7445.29497 10733.2 47.367510796.8445.9152710823.1242.8908410925.0646.64474
#Mann= 3 , 0 , 0
9074.947  0.0812       09074.947  0.0812       010925.06  0.0812       0
#XS Ineff= 2 , 0
       09892.342        10325.26       0
Bank Sta=9074.947,10925.06
Exp/Cntr=0.3,0.1

Type RM Length L Ch R = 1 , 12420.9,226.035900,226.035900,226.035900
XS GIS Cut Line= 6
776978.799127877861955.954552367777164.952426225861724.765953481
777296.950603873861569.519061819777860.957511187 860959.11928162
778046.955907077860744.309147701778256.716489047860271.838647291
#Sta/Elev= 30
 9059.3260.705579132.98759.976829150.41753.062939163.25651.379679240.28948.56886
9342.99949.69103 9371.6546.379999447.71444.206979616.76448.003089673.67245.98315
9700.59147.477319754.42843.755849868.49440.414429970.64242.3952510001.2130.41699
10014.95 37.134610043.56 39.456410111.1437.6855910204.2439.28812 10233.938.13691
10288.2739.4857310427.4138.8914110503.1340.8357110533.6539.4934810783.8438.85621
10827.6136.0991910937.0235.9989310980.79 37.948811064.6847.7202311192.1349.73182
#Mann= 3 , 0 , 0
 9059.32  0.0738       0 9059.32  0.0738       011192.13  0.0738       0
#XS Ineff= 2 , 0
       0 9949.31        10349.28       0
Bank Sta=9059.32,11192.13
Exp/Cntr=0.3,0.1