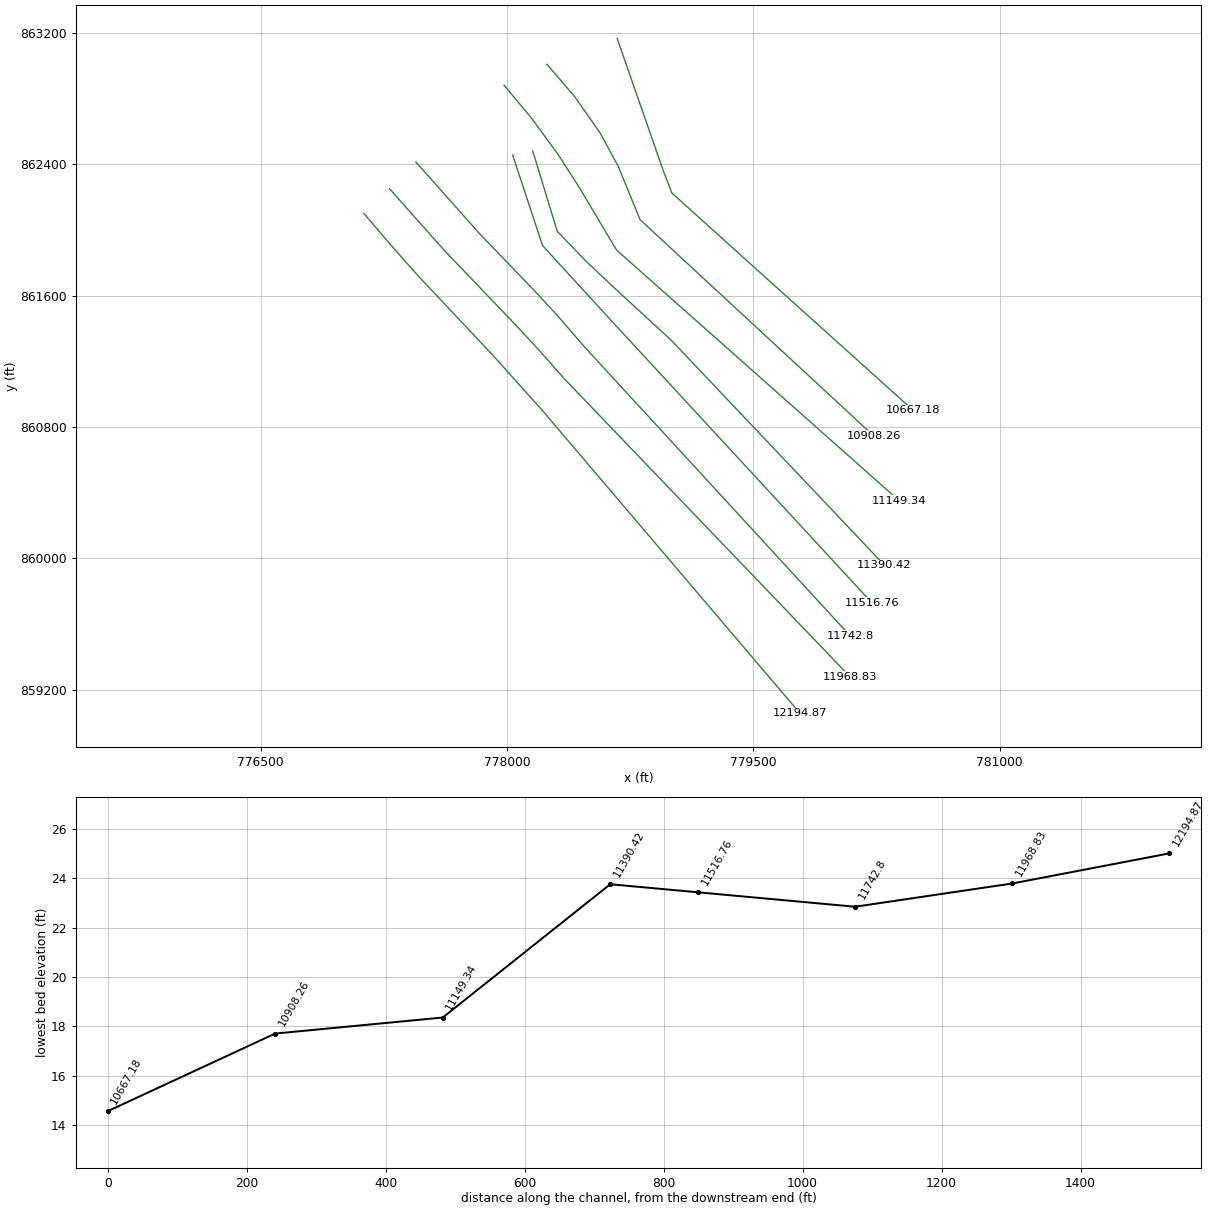
HEC-RAS study 16016_ras.prj: 16016

--- 16016_ras.g01 (geometry) --- (continued)

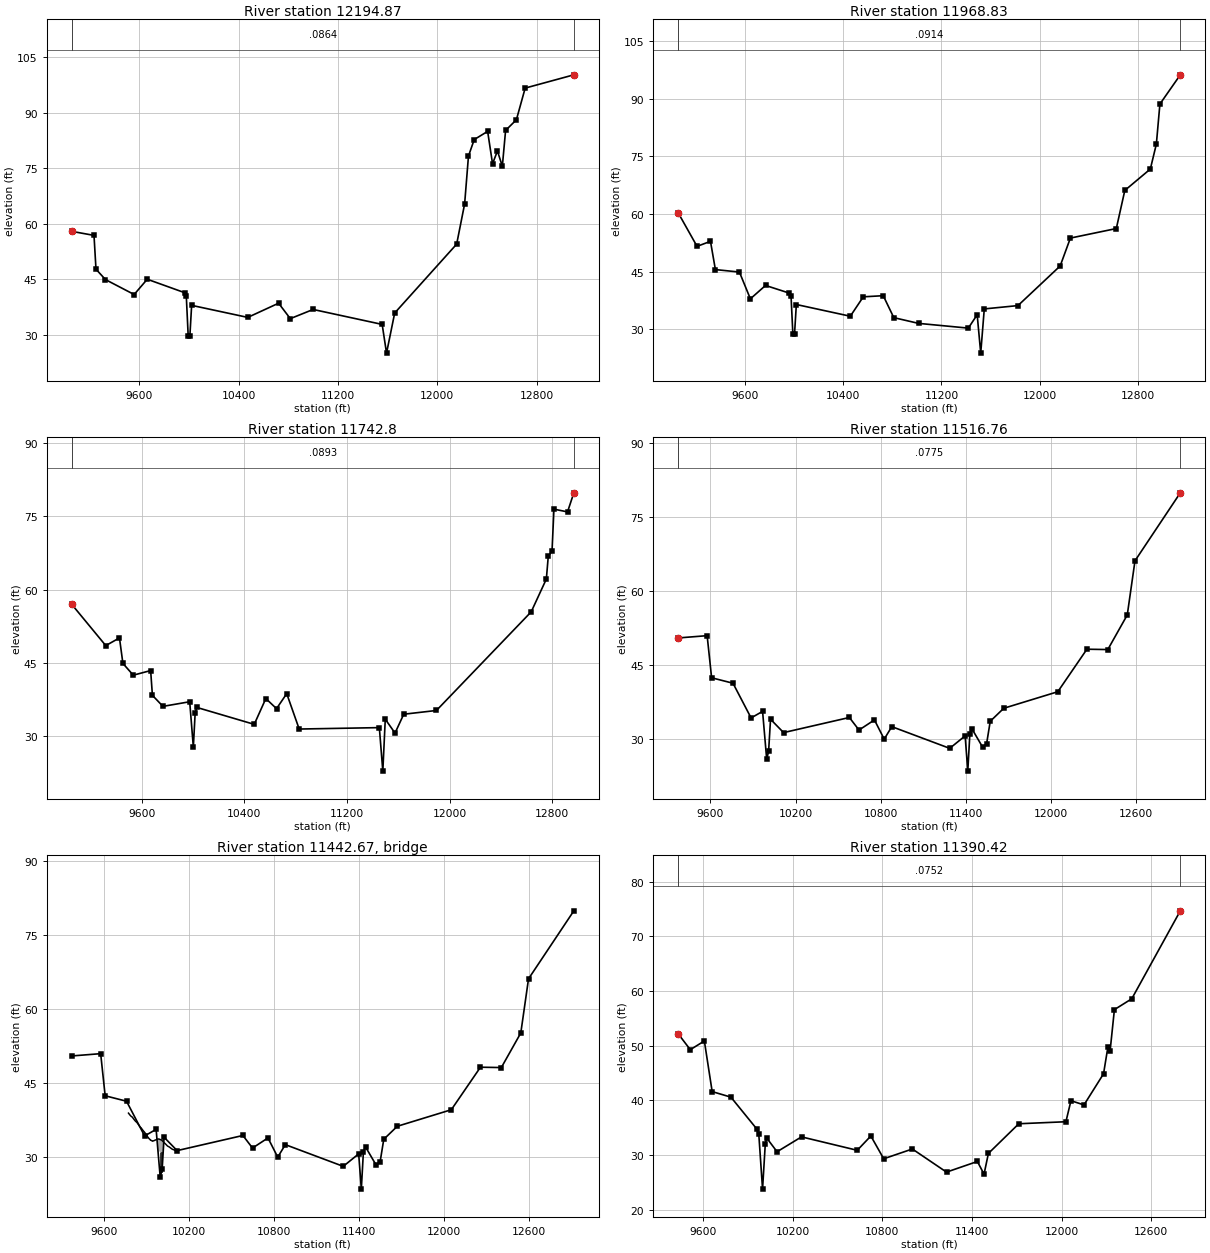
Type RM Length L Ch R = 1 ,12194.87,226.036000,226.036000,226.036000
XS GIS Cut Line= 6
777128.890738726862101.459241584777280.272655696861923.049138293
777458.003458619861722.376313165777913.901215404861237.472501606
778219.676467299860896.484230265779784.494266808  859056.5608695
#Sta/Elev= 30
9057.86657.929479236.82956.839159252.78447.694689329.31544.88496 9559.9140.85252
 9665.3644.983819967.52941.332599979.48140.561359995.08529.5489410008.5729.73889
 10022.637.9219610474.3934.66481 10722.6 38.502810816.7434.3299611000.4436.81101
11556.1232.7698711591.2625.00457 11656.9  35.84912155.7554.4804112219.8465.35091
12250.7178.2816212297.0282.7471112405.0684.9620612444.5576.2022612483.9379.67263
12523.3275.5179212549.5785.22447 12636.688.11117 12707.196.6691213098.88100.2547
#Mann= 3 , 0 , 0
9057.866  0.0864       09057.866  0.0864       013098.88  0.0864       0
#XS Ineff= 2 , 0
       09945.047        10373.15       0
Bank Sta=9057.866,13098.88
Exp/Cntr=0.3,0.1

Type RM Length L Ch R = 1 ,11968.83,226.035900,226.035900,226.035900
XS GIS Cut Line= 6
777283.960172743862252.428168163777618.409695387861876.308126017
778051.917470843861423.059100583 778195.02359286861268.795514867
 778349.22254476 861094.17608352 780090.04982239859278.783091709
#Sta/Elev= 30
9056.582 60.29999209.81551.587059319.18852.897619359.13745.537739554.83644.89846
9644.08637.921619767.65641.41217 9962.3339.401429975.23238.686599990.15228.77393
10004.0128.8918510018.4436.4458510457.9233.3925410563.6838.4474710726.3338.73921
10812.2133.0241311014.4931.5286711419.0430.2974811491.2833.7788611520.17 23.7855
11549.0735.2965611823.59 36.164512167.2246.4844112250.3553.7436512624.4356.22747
 12693.766.1516412901.5271.7179812950.5478.2188112979.4488.6405813145.6796.25206
#Mann= 3 , 0 , 0
9056.582  0.0914       09056.582  0.0914       013145.67  0.0914       0
#XS Ineff= 2 , 0
       09940.664        10398.47       0
Bank Sta=9056.582,13145.67
Exp/Cntr=0.3,0.1

Type RM Length L Ch R = 1 , 11742.8,226.036000,226.036000,226.036000
XS GIS Cut Line= 6
777445.524598062862413.949810848 777831.84615171861979.400091991
778181.609714508861615.458845362778310.107801139861475.912383586
778471.386921018861289.205035672 780090.04982239859528.783091724
#Sta/Elev= 30
9054.663 56.96299319.72648.527479426.44450.100099453.39544.874019534.24642.47756
9669.58243.419039683.297 38.35459765.58336.094679974.05337.0406610002.3727.76422
10016.7134.8218410029.9335.8737510477.1732.4142110567.5537.6959910650.9635.62706
 10730.438.7006910827.5631.4547611452.4531.7459611479.6222.8434411498.6733.46867
11574.7230.6281611642.6434.4865911897.5835.25406 12636.355.43636 12754.562.15512
12769.2766.7699312798.8267.9030112813.5976.44831 12919.675.88921 12968.879.78897
#Mann= 3 , 0 , 0
9054.663  0.0893       09054.663  0.0893       0 12968.8  0.0893       0
#XS Ineff= 2 , 0
       09945.782        10424.91       0
Bank Sta=9054.663,12968.8
Exp/Cntr=0.3,0.1

Type RM Length L Ch R = 1 ,11516.76,126.339100,126.339100,126.339100
XS GIS Cut Line= 4
778033.875094324862458.553552732778216.493450969   861905.616283
778668.088402629861412.674763754780221.994266808859730.171980605
#Sta/Elev= 30
9372.82750.433089576.66350.895799608.25742.358349759.05741.251019886.60434.21436
9967.73335.543319996.66225.8444510010.2227.4610910023.7933.9549910115.7731.23773
10579.8334.3056210647.7331.7580710756.63 33.810410825.4629.9130310879.1432.44809
11287.5128.0474911396.4130.5769911415.0223.4284111429.7631.01404 11444.531.99289
11518.9228.3325211547.6728.9729711573.3733.5360211668.6636.1717912049.8139.52857
12255.1448.1481712402.5348.0778412539.8555.09781 12594.3 66.074812913.9679.85847
#Mann= 3 , 0 , 0
9372.827  0.0775       09372.827  0.0775       012913.96  0.0775       0
#XS Ineff= 2 , 0
       09946.764        10446.97       0
Bank Sta=9372.827,12913.96
Exp/Cntr=0.3,0.1

Type RM Length L Ch R = 3 ,11442.67,,,
BEGIN DESCRIPTION:
END DESCRIPTION:
Bridge Culvert--1,0,-1,-1, 0
Deck Dist Width WeirC Skew NumUp NumDn MinLoCord MaxHiCord MaxSubmerge Is_Ogee
42.819550,40.700000,2.6,0, 53, 53, , , 0.95, 0, 0,0,,
 9772.87 9780.92 9791.48 9799.37 9802.03 9812.58 9823.14 9830.65 9833.69 9844.25
 9854.80 9861.93 9865.35 9875.91 9886.46 9893.21 9897.02 9907.57 9918.12 9924.48
 9928.68 9929.51 9941.71 9942.31 9954.96 9957.56 9968.20 9972.80 9981.45 9985.75
 9985.75 9988.05 9994.7010003.3010007.9410014.2510014.2510018.5510021.1910033.79
10034.4410047.6810049.0410060.9310064.2910074.1810079.5410087.4210094.7910100.67
10110.0310113.9210122.50
   38.84   38.53   38.19   38.04   37.94   37.53   37.17   36.99   36.89   36.47
   36.03   35.85   35.71   35.30   34.95   34.68   34.51   34.05   33.67   33.49
   33.35   33.36   33.17   33.15   33.28   33.33   33.44   33.55   33.59   33.59
   33.59   33.59   33.51   33.41   33.34   33.15   33.15   33.02   32.93   32.59
   32.58   32.18   32.15   31.97   31.89   31.68   31.56   31.45   31.38   31.29
   31.13   31.03   30.88
 -961.16 -961.47 -961.81 -961.96 -962.06 -962.47 -962.83 -963.01 -963.11 -963.53
 -963.97 -964.15 -964.29 -964.70 -965.05 -965.32 -965.49 -965.95 -966.33 -966.51
 -966.65 -966.64 -966.83 -966.85 -966.72 -966.67 -966.56 -966.45 -966.41 -966.41
   31.09   31.09   31.01   30.91   30.84   30.65 -966.85 -966.98 -967.07 -967.41
 -967.42 -967.82 -967.85 -968.03 -968.11 -968.32 -968.44 -968.55 -968.62 -968.71
 -968.87 -968.97 -969.12
 9772.87 9780.92 9791.48 9799.37 9802.03 9812.58 9823.14 9830.65 9833.69 9844.25
 9854.80 9861.93 9865.35 9875.91 9886.46 9893.21 9897.02 9907.57 9918.12 9924.48
 9928.68 9929.51 9941.71 9942.31 9954.96 9957.56 9968.20 9972.80 9981.45 9985.75
 9985.75 9988.05 9994.7010003.3010007.9410014.2510014.2510018.5510021.1910033.79
10034.4410047.6810049.0410060.9310064.2910074.1810079.5410087.4210094.7910100.67
10110.0310113.9210122.50
   38.84   38.53   38.19   38.04   37.94   37.53   37.17   36.99   36.89   36.47
   36.03   35.85   35.71   35.30   34.95   34.68   34.51   34.05   33.67   33.49
   33.35   33.36   33.17   33.15   33.28   33.33   33.44   33.55   33.59   33.59
   33.59   33.59   33.51   33.41   33.34   33.15   33.15   33.02   32.93   32.59
   32.58   32.18   32.15   31.97   31.89   31.68   31.56   31.45   31.38   31.29
   31.13   31.03   30.88
 -961.16 -961.47 -961.81 -961.96 -962.06 -962.47 -962.83 -963.01 -963.11 -963.53
 -963.97 -964.15 -964.29 -964.70 -965.05 -965.32 -965.49 -965.95 -966.33 -966.51
 -966.65 -966.64 -966.83 -966.85 -966.72 -966.67 -966.56 -966.45 -966.41 -966.41
   31.09   31.09   31.01   30.91   30.84   30.65 -966.85 -966.98 -967.07 -967.41
 -967.42 -967.82 -967.85 -968.03 -968.11 -968.32 -968.44 -968.55 -968.62 -968.71
 -968.87 -968.97 -969.12
Pier Skew, UpSta & Num, DnSta & Num=  ,9994.92, 2 ,9994.92, 2 , 0 , 0 , 0 ,,
    2.00    2.00
 -966.50   33.50
    2.00    2.00
 -966.50   33.50
Pier Skew, UpSta & Num, DnSta & Num=  ,10005.08, 2 ,10005.08, 2 , 0 , 0 , 0 ,,
    2.00    2.00
 -966.62   33.38
    2.00    2.00
 -966.62   33.38
BR Coef=-1 , 0 , 0 ,, 0 ,,,0.8,0,1,0,
WSPro=,,,, 1 ,,,, 0 ,,,, 0 ,,,,-1 ,-1 ,-1 , 0 , 0 , 0 , 0 , 0
BC Design=,, 0 ,, 0 ,,,,,,

Type RM Length L Ch R = 1 ,11390.42,241.079800,241.079800,241.079800
XS GIS Cut Line= 6
778156.475295037862482.187326387 778305.66349113861993.263634324
778482.916793346861808.624777809778668.088402629861634.619811252
779003.537129819861325.751559705780298.383155704859959.338647291
#Sta/Elev= 30
9434.65552.156189515.35649.263249609.45250.857469661.72841.59508 9787.1940.58117
9959.31534.788159973.75533.778049998.87523.7547410017.0731.99298 10026.633.10849
10095.9130.5931710259.5333.3150310632.4830.8570310723.5533.4739210809.6429.30819
11001.2331.0959311229.77  26.86611436.4228.8145511480.9926.4859411510.0630.28465
 11713.635.7140112028.8236.0823312062.5239.9308212149.7539.1567412280.5944.84998
12309.6749.72596 12324.248.9612912353.2856.5902912469.5958.5767312794.3574.66499
#Mann= 3 , 0 , 0
9434.655  0.0752       09434.655  0.0752       012794.35  0.0752       0
#XS Ineff= 2 , 0
       09940.459        10454.53       0
Bank Sta=9434.655,12794.35
Exp/Cntr=0.3,0.1

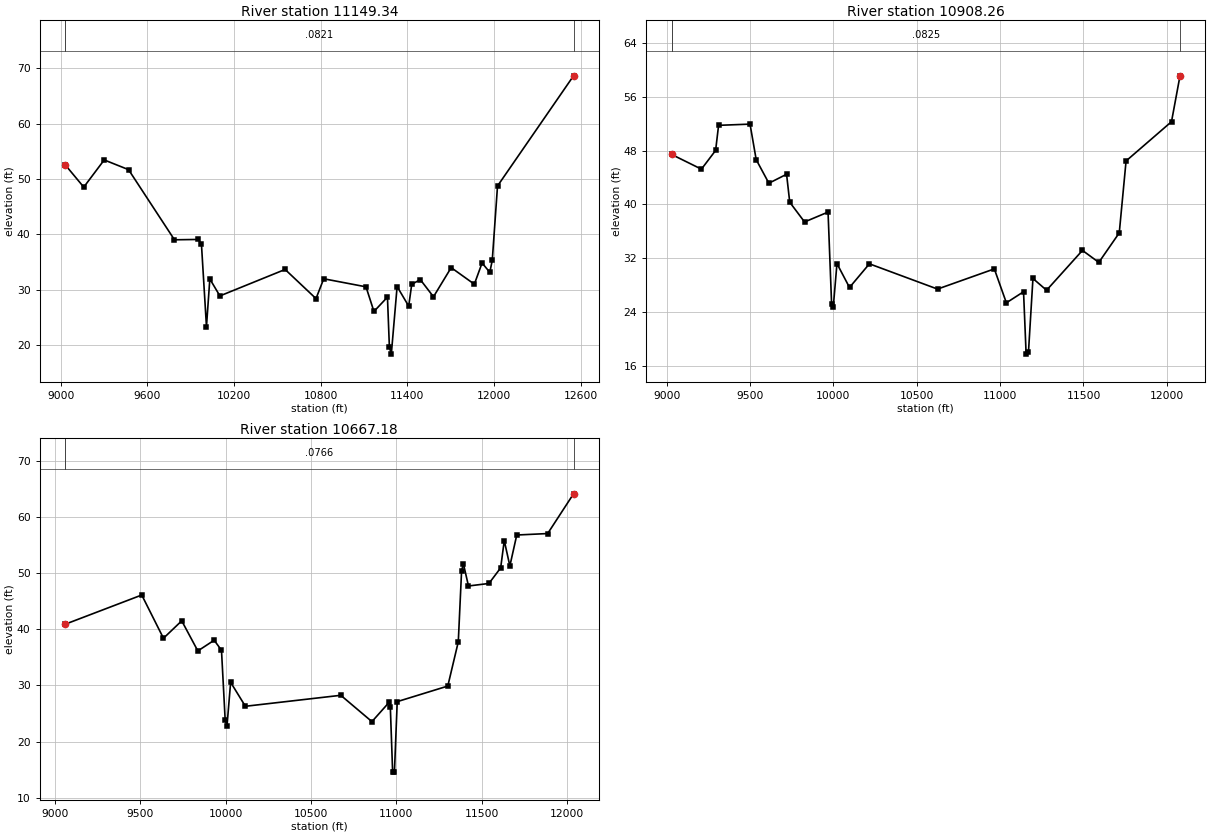
Type RM Length L Ch R = 1 ,11149.34,241.079700,241.079700,241.079700
XS GIS Cut Line= 6
777981.900698036862882.472635403778148.919232875862682.390834019
778307.236598819862466.121082634778434.355295241862269.386025265
778667.011992484861878.830219582780388.660933465860351.699758381
#Sta/Elev= 30
9031.19652.563359159.65748.532759301.13953.448949469.61351.692579787.52939.01592
9950.82939.078559974.14538.2841410009.0723.3293210032.3331.9389410102.0828.87335
10553.5233.65545 10767.428.3874510820.8631.9719711113.5230.5153611168.4126.06041
11261.9828.6583111275.3519.6417111288.7118.3534611328.8130.5685711409.0227.02353
11429.9830.9626711489.2231.8237911580.6828.7196111703.0933.98716 11863.5 30.9925
11916.9734.8264111970.4433.1401511987.5635.30855 12023.9 48.742412550.1268.64843
#Mann= 3 , 0 , 0
9031.196  0.0821       09031.196  0.0821       012550.12  0.0821       0
#XS Ineff= 2 , 0
       0                10443.66       0
Bank Sta=9031.196,12550.12
Exp/Cntr=0.3,0.1

Type RM Length L Ch R = 1 ,10908.26,241.079800,241.079800,241.079800
XS GIS Cut Line= 6
 778243.60430491863009.445000544778414.170538932862810.340672404
778567.608579159862590.693486899778679.158471048862384.835616454
778810.090292841862063.895359233780232.410933465860747.533091724
#Sta/Elev= 30
9029.66647.416319208.07345.230389293.288 48.0187 9311.0351.753479499.73251.93286
9536.66946.644399612.78443.139049718.92244.471129737.88440.312899826.789  37.373
9967.695  38.8439989.101 25.1061    999924.6988810021.1431.1755210096.3827.62288
10215.7231.1432410624.4827.3843710965.1230.3877711037.3425.3395311140.3926.98473
11155.8817.7039911169.8417.9618211196.7628.9594911278.5127.2101311493.73 33.1397
 11591.931.3553411714.5335.7473911755.4146.4515612027.9252.2946712078.8959.12052
#Mann= 3 , 0 , 0
9029.666  0.0825       09029.666  0.0825       012078.89  0.0825       0
#XS Ineff= 2 , 0
       0                10391.42       0
Bank Sta=9029.666,12078.89
Exp/Cntr=0.3,0.1

Type RM Length L Ch R = 1 ,10667.18,140.246000,140.246000,140.246000
XS GIS Cut Line= 6
778670.590809196863168.017988786778950.277183861862365.414421275
778982.242295563862282.495985866779003.176590532862227.000417084
779430.327600151861841.283091724780471.994266808860903.783091724
#Sta/Elev= 30
9061.77140.901989509.73846.104739636.81538.401629743.72841.507159838.02136.14399
9933.58938.050319976.45736.259079997.891 23.910110008.5922.7566410029.9630.55852
10116.2426.2852810674.7128.2412610856.9623.5524710958.7327.0305810964.5926.16038
10978.0514.5862910988.6314.5564811004.9527.1124611300.9329.8882911362.34 37.7662
11381.6650.4320411392.2451.6653711422.0247.7121111541.7248.1607611610.3750.94073
11631.4155.8034411664.1851.2793911704.5456.7921511885.5457.0502612036.8464.12758
#Mann= 3 , 0 , 0
9061.771  0.0766       09061.771  0.0766       012036.84  0.0766       0
#XS Ineff= 2 , 0
       09929.997         10316.3       0
Bank Sta=9061.771,12036.84
Exp/Cntr=0.3,0.1