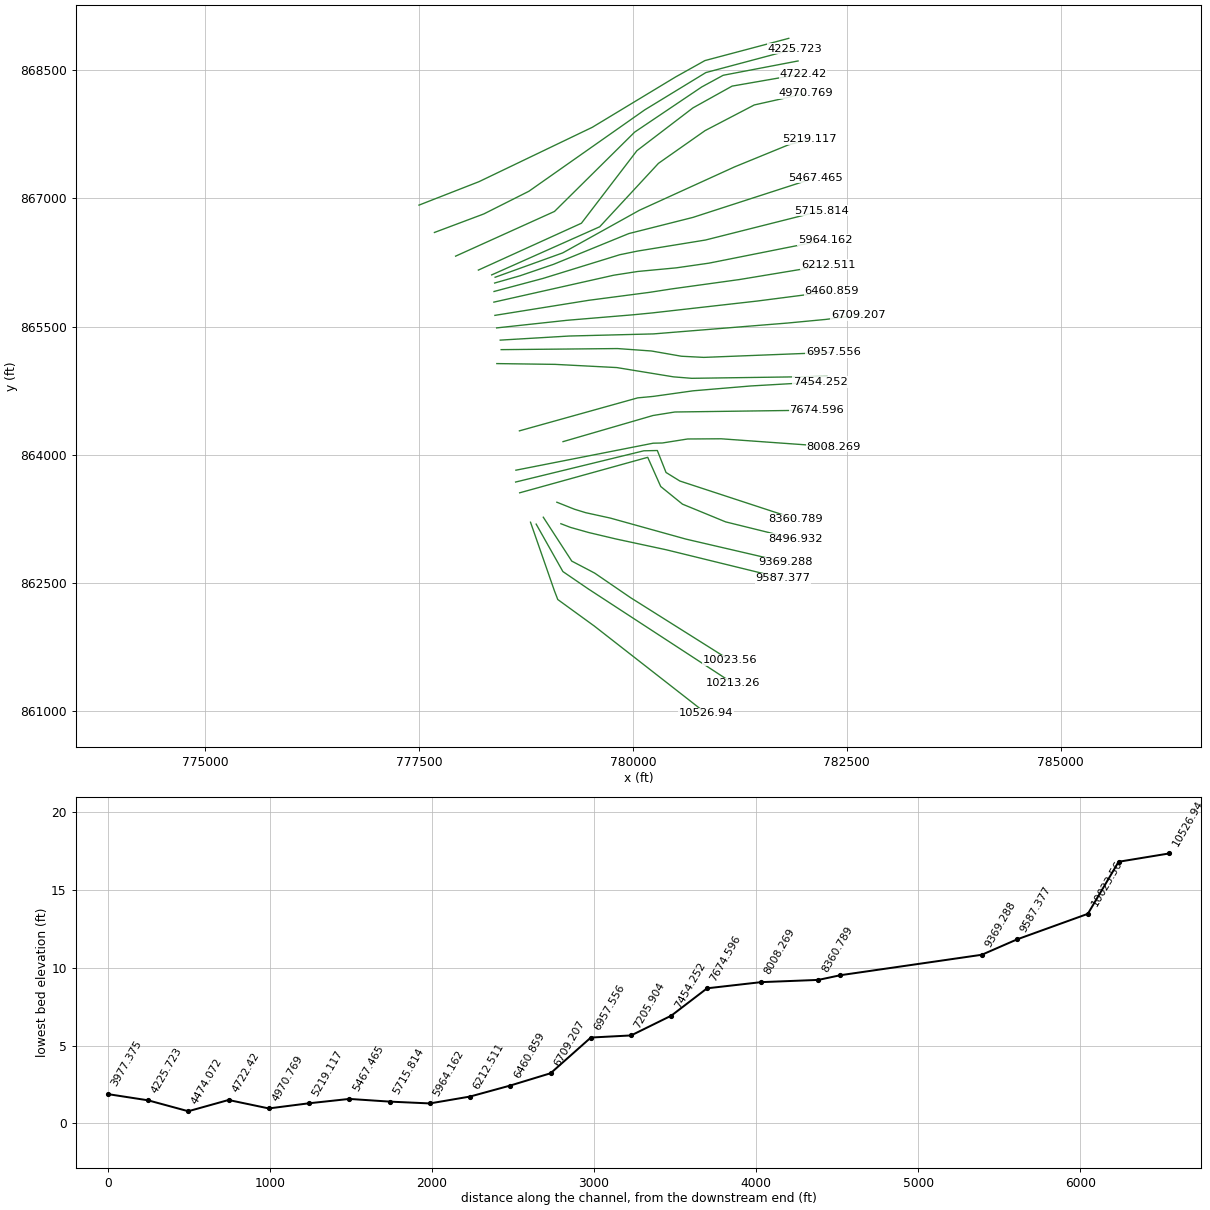
HEC-RAS study 16016_ras.prj: 16016

--- 16016_ras.g01 (geometry) --- (continued)

Type RM Length L Ch R = 3 , 10599.9,,,
BEGIN DESCRIPTION:
END DESCRIPTION:
Bridge Culvert--1,0,-1,-1, 0
Deck Dist Width WeirC Skew NumUp NumDn MinLoCord MaxHiCord MaxSubmerge Is_Ogee
49.923000,40.400000,2.6,0, 54, 54, , , 0.95, 0, 0,0,,
 9770.88 9771.54 9782.16 9792.79 9798.03 9803.41 9814.04 9824.67 9827.60 9835.29
 9845.92 9856.55 9857.16 9867.17 9877.80 9886.73 9888.42 9899.05 9909.68 9916.30
 9920.30 9930.93 9941.55 9945.87 9952.18 9962.81 9973.43 9975.44 9980.66 9984.08
 9984.90 9984.90 9994.7810003.8810005.4710015.1010015.1010016.1710026.8610032.07
10037.5610044.4410049.4810052.3810063.6210066.5210077.7710080.6610091.9110094.80
10106.0510108.9510120.1910121.51
   36.14   36.13   36.08   36.03   35.99   35.93   35.83   35.85   35.82   35.69
   35.61   35.88   35.88   35.85   35.70   35.71   35.71   35.60   35.72   35.74
   35.71   35.51   35.35   35.28   35.13   34.90   34.60   34.55   34.40   34.29
   34.27   34.27   34.02   33.67   33.60   33.00   33.00   32.93   32.06   31.71
   31.35   30.77   30.26   30.03   29.21   28.94   28.60   28.50   27.64   27.36
   26.32   26.21   25.97   25.98
 -963.86 -963.87 -963.92 -963.97 -964.01 -964.07 -964.17 -964.15 -964.18 -964.31
 -964.39 -964.12 -964.12 -964.15 -964.30 -964.29 -964.29 -964.40 -964.28 -964.26
 -964.29 -964.49 -964.65 -964.72 -964.87 -965.10 -965.40 -965.45 -965.60 -965.71
 -965.73   31.77   31.52   31.17   31.10   30.50 -967.00 -967.07 -967.94 -968.29
 -968.65 -969.23 -969.74 -969.97 -970.79 -971.06 -971.40 -971.50 -972.36 -972.64
 -973.68 -973.79 -974.03 -974.02
 9770.88 9771.54 9782.16 9792.79 9798.03 9803.41 9814.04 9824.67 9827.60 9835.29
 9845.92 9856.55 9857.16 9867.17 9877.80 9886.73 9888.42 9899.05 9909.68 9916.30
 9920.30 9930.93 9941.55 9945.87 9952.18 9962.81 9973.43 9975.44 9980.66 9984.08
 9984.90 9984.90 9994.7810003.8810005.4710015.1010015.1010016.1710026.8610032.07
10037.5610044.4410049.4810052.3810063.6210066.5210077.7710080.6610091.9110094.80
10106.0510108.9510120.1910121.51
   36.14   36.13   36.08   36.03   35.99   35.93   35.83   35.85   35.82   35.69
   35.61   35.88   35.88   35.85   35.70   35.71   35.71   35.60   35.72   35.74
   35.71   35.51   35.35   35.28   35.13   34.90   34.60   34.55   34.40   34.29
   34.27   34.27   34.02   33.67   33.60   33.00   33.00   32.93   32.06   31.71
   31.35   30.77   30.26   30.03   29.21   28.94   28.60   28.50   27.64   27.36
   26.32   26.21   25.97   25.98
 -963.86 -963.87 -963.92 -963.97 -964.01 -964.07 -964.17 -964.15 -964.18 -964.31
 -964.39 -964.12 -964.12 -964.15 -964.30 -964.29 -964.29 -964.40 -964.28 -964.26
 -964.29 -964.49 -964.65 -964.72 -964.87 -965.10 -965.40 -965.45 -965.60 -965.71
 -965.73   31.77   31.52   31.17   31.10   30.50 -967.00 -967.07 -967.94 -968.29
 -968.65 -969.23 -969.74 -969.97 -970.79 -971.06 -971.40 -971.50 -972.36 -972.64
 -973.68 -973.79 -974.03 -974.02
Pier Skew, UpSta & Num, DnSta & Num=  ,9994.63, 2 ,9994.63, 2 , 0 , 0 , 0 ,,
    2.00    2.00
 -965.98   34.02
    2.00    2.00
 -965.98   34.02
Pier Skew, UpSta & Num, DnSta & Num=  ,10005.37, 2 ,10005.37, 2 , 0 , 0 , 0 ,,
    2.00    2.00
 -966.39   33.61
    2.00    2.00
 -966.39   33.61
BR Coef=-1 , 0 , 0 ,, 0 ,,,0.8,0,1,0,
WSPro=,,,, 1 ,,,, 0 ,,,, 0 ,,,,-1 ,-1 ,-1 , 0 , 0 , 0 , 0 , 0
BC Design=,, 0 ,, 0 ,,,,,,

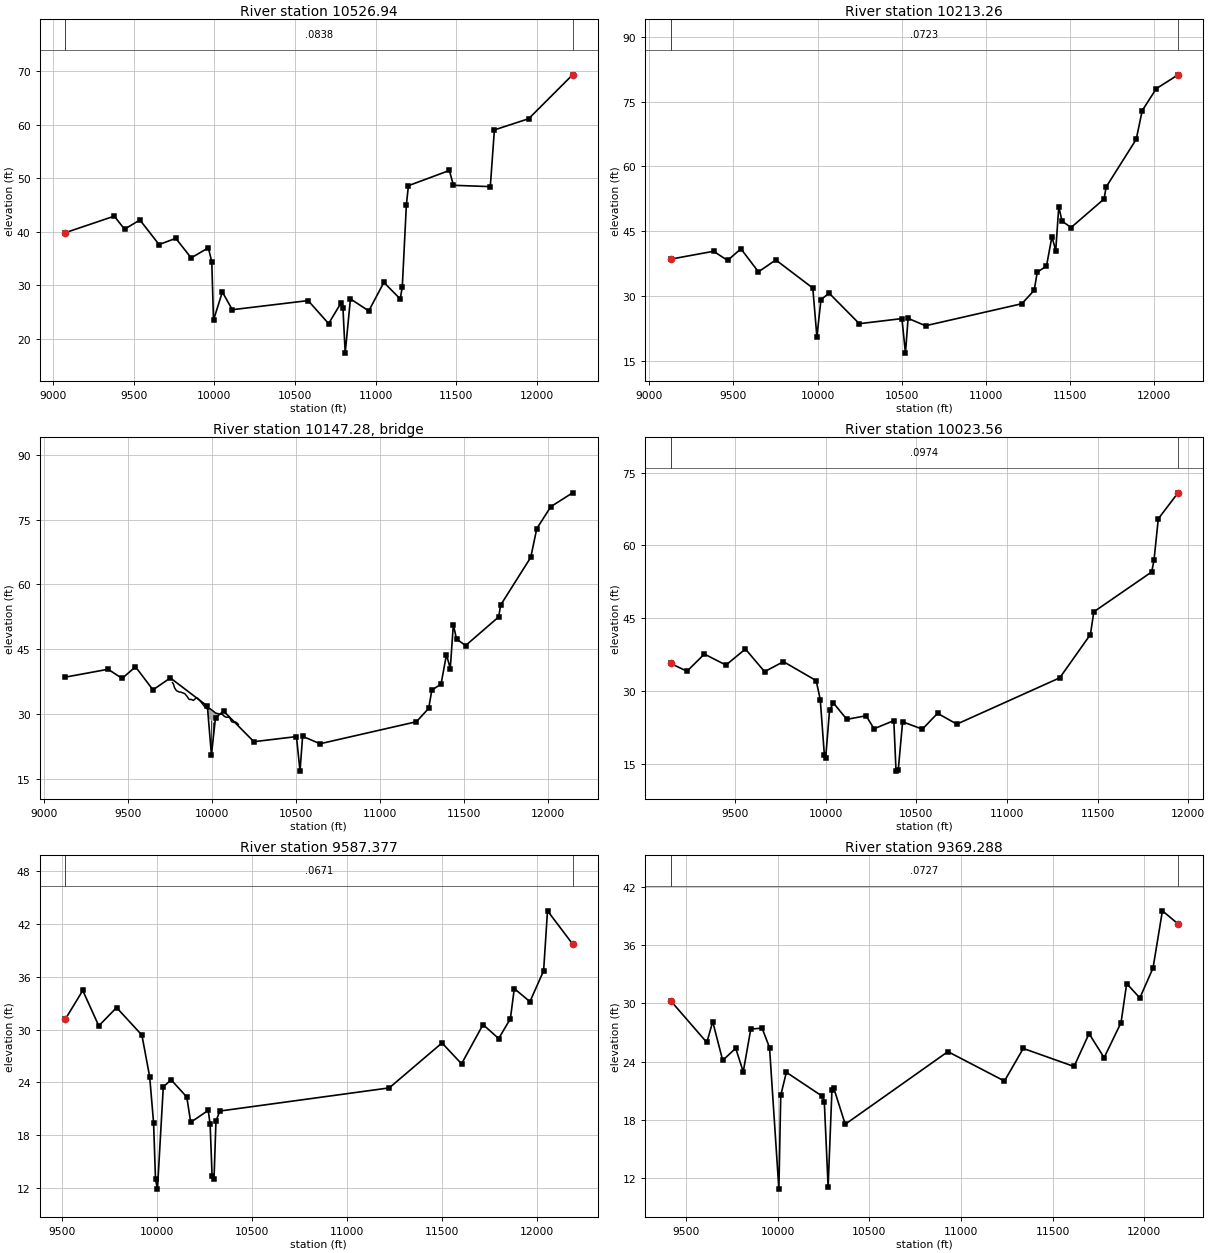
Type RM Length L Ch R = 1 ,10526.94,313.674400,313.674400,313.674400
XS GIS Cut Line= 6
778803.461784886863212.549274908779082.612054633862411.484143944
779114.081308173862329.854371788779122.064718233862308.690827267
779548.871527808861998.905605541 780856.97690572860977.567813949
#Sta/Elev= 30
9075.11539.856059379.623 42.95539443.16240.51746 9538.47 42.24149657.18137.64966
9760.855 38.80839856.16335.161119962.52637.03327 9983.96 34.44939994.67723.53578
10049.5128.78359 10111.325.4753710581.3727.1772810708.2422.8776810784.3726.70513
10797.0525.82633   1081117.36409 10843.527.4902910957.2425.2567911050.7930.57553
11152.2927.4824611164.9829.7496211190.3545.1000111203.0448.6496411456.7851.48864
11482.1548.7179111710.5248.4718311735.8959.0646411948.4561.1582612220.5169.35822
#Mann= 3 , 0 , 0
9075.115  0.0838       09075.115  0.0838       012220.51  0.0838       0
#XS Ineff= 2 , 0
       09935.543        10284.16       0
Bank Sta=9075.115,12220.51
Exp/Cntr=0.3,0.1

Type RM Length L Ch R = 1 ,10213.26,189.706800,189.706800,189.706800
XS GIS Cut Line= 4
778869.563711256863190.241425052779182.063711256862635.553925067
 779476.45900926862434.301871821781173.383155704861327.394202828
#Sta/Elev= 30
9125.91738.559789381.46940.384639464.789 38.27129544.45440.955839648.434 35.6221
9751.73438.383169972.05931.874379996.28620.5930810020.5129.1823110068.9730.70101
10248.7823.6322310502.2824.8149610523.3816.8270110538.8924.8760210642.7823.16055
11216.1228.2533411289.3331.3595711307.6435.5666311362.5536.9451811394.9643.77681
11417.4640.5192411435.7650.7379311454.6647.3663411508.9845.8811111705.3952.48824
11717.3355.2395111896.4266.2679211932.2472.9196912015.8177.9906812145.2281.19339
#Mann= 3 , 0 , 0
9125.917  0.0723       09125.917  0.0723       012145.22  0.0723       0
#XS Ineff= 2 , 0
       09893.538        10216.58       0
Bank Sta=9125.917,12145.22
Exp/Cntr=0.3,0.1

Type RM Length L Ch R = 3 ,10147.28,,,
BEGIN DESCRIPTION:
END DESCRIPTION:
Bridge Culvert--1,0,-1,-1, 0
Deck Dist Width WeirC Skew NumUp NumDn MinLoCord MaxHiCord MaxSubmerge Is_Ogee
69.603400,50.500000,2.6,0, 33, 33, , , 0.95, 0, 0,0,,
 9764.28 9771.15 9776.48 9787.89 9804.62 9813.90 9838.09 9851.32 9863.79 9876.26
 9888.73 9905.03 9913.67 9926.15 9955.23 9971.96 9978.20 9978.20 9988.5010021.80
10021.8010036.1410039.8610060.4710071.6310082.7910093.9510105.1110116.2710129.99
10138.5910149.7510156.62
   37.32   36.87   36.14   35.44   35.12   35.11   34.73   34.11   33.39   33.41
   33.19   33.72   33.71   33.20   31.78   31.20   31.22   31.22   31.26   30.26
   30.26   30.12   30.02   29.99   29.56   29.30   29.32   29.22   28.27   28.08
   28.22   27.91   27.63
 -962.68 -963.13 -963.86 -964.56 -964.88 -964.89 -965.27 -965.89 -966.61 -966.59
 -966.81 -966.28 -966.29 -966.80 -968.22 -968.80 -968.78   28.72   28.76   27.76
 -969.74 -969.88 -969.98 -970.01 -970.44 -970.70 -970.68 -970.78 -971.73 -971.92
 -971.78 -972.09 -972.37
 9764.28 9771.15 9776.48 9787.89 9804.62 9813.90 9838.09 9851.32 9863.79 9876.26
 9888.73 9905.03 9913.67 9926.15 9955.23 9971.96 9978.20 9978.20 9988.5010021.80
10021.8010036.1410039.8610060.4710071.6310082.7910093.9510105.1110116.2710129.99
10138.5910149.7510156.62
   37.32   36.87   36.14   35.44   35.12   35.11   34.73   34.11   33.39   33.41
   33.19   33.72   33.71   33.20   31.78   31.20   31.22   31.22   31.26   30.26
   30.26   30.12   30.02   29.99   29.56   29.30   29.32   29.22   28.27   28.08
   28.22   27.91   27.63
 -962.68 -963.13 -963.86 -964.56 -964.88 -964.89 -965.27 -965.89 -966.61 -966.59
 -966.81 -966.28 -966.29 -966.80 -968.22 -968.80 -968.78   28.72   28.76   27.76
 -969.74 -969.88 -969.98 -970.01 -970.44 -970.70 -970.68 -970.78 -971.73 -971.92
 -971.78 -972.09 -972.37
Pier Skew, UpSta & Num, DnSta & Num=  ,9992.40, 2 ,9992.40, 2 , 0 , 0 , 0 ,,
    2.00    2.00
 -968.85   31.15
    2.00    2.00
 -968.85   31.15
Pier Skew, UpSta & Num, DnSta & Num=  ,10007.60, 2 ,10007.60, 2 , 0 , 0 , 0 ,,
    2.00    2.00
 -969.33   30.67
    2.00    2.00
 -969.33   30.67
BR Coef=-1 , 0 , 0 ,, 0 ,,,0.8,0,1,0,
WSPro=,,,, 1 ,,,, 0 ,,,, 0 ,,,,-1 ,-1 ,-1 , 0 , 0 , 0 , 0 , 0
BC Design=,, 0 ,, 0 ,,,,,,

Type RM Length L Ch R = 1 ,10023.56,436.178000,436.178000,436.178000
XS GIS Cut Line= 6
778952.897044599863270.970591724779285.885024697862757.764921516
779485.553946197862653.384682611779554.914659888862616.660726041
779972.496079803862330.777393714781137.090744406861597.677160621
#Sta/Elev= 30
9145.86735.656659236.42834.061359331.79237.601169450.99835.331749558.28338.63496
9664.14933.966739767.92136.035179948.46532.128029971.03328.201129993.64816.81198
 10000.816.17629 10022.226.0264810043.5927.5127710117.4724.1466110223.6824.88738
10267.55 22.205910376.6223.8858910388.7413.4802810400.8613.63694 10425.123.64467
10534.1722.1264610617.7225.3903210724.0623.1643911291.6532.7034711460.5941.62751
11479.3646.3033811798.47 54.518511811.1756.90813 11834.865.4617311943.6270.81685
#Mann= 3 , 0 , 0
9145.867  0.0974       09145.867  0.0974       011943.62  0.0974       0
#XS Ineff= 2 , 0
       09894.066        10219.21       0
Bank Sta=9145.867,11943.62
Exp/Cntr=0.3,0.1

Type RM Length L Ch R = 1 ,9587.377,218.089000,218.089000,218.089000
XS GIS Cut Line= 6
779158.354402006863195.041569829779270.475530088863152.008650243
779485.031078398863091.714296803 779802.76866293863016.542121306
780392.133155704862889.894202828781753.244266838  862556.5608695
#Sta/Elev= 30
9516.04631.151589608.85434.443829693.227 30.41629786.897 32.50139920.46729.36443
9961.40524.620789981.874 19.41919992.10912.9636710002.3511.8390710033.1223.46486
10074.1524.2818910156.9222.3243410177.6319.4398710269.78 20.796310280.0119.21557
10290.2413.3698910300.4713.0105610310.6919.5859610331.1520.7250711223.8523.35859
11501.8328.4740811604.7926.0990711718.0430.56383 11800.428.9731711862.1831.22945
11882.7734.6646711965.1333.17031 12037.236.6764612057.7943.5084812189.8239.73903
#Mann= 3 , 0 , 0
9516.046  0.0671       09516.046  0.0671       012189.82  0.0671       0
#XS Ineff= 2 , 0
       09894.659        10356.44       0
Bank Sta=9516.046,12189.82
Exp/Cntr=0.3,0.1

Type RM Length L Ch R = 1 ,9369.288,872.356000,872.356000,872.356000
XS GIS Cut Line= 6
779111.451554447863446.296955958779317.080324411   863364.369507
 779448.48093164863323.989229754779734.110393316863261.460124984
 780621.29982236863014.894202814781787.966489017  862744.0608695
#Sta/Elev= 30
9414.92330.267919612.758  25.9599644.66328.110669699.27624.114459770.18925.36658
  9811.422.937579852.56827.340569914.13327.441949954.926 25.430710005.9210.84751
10016.1320.5117610046.7522.8863810243.6320.4087710254.0119.7970110274.7711.08334
10295.5321.02644 10305.921.2369810368.1817.5335110928.6525.0165811237.2621.98515
11339.9225.34569 11617.123.4870411699.2326.8715911781.3524.3929811873.7528.00842
11904.5432.0308311976.4130.5493112048.2733.62718 12099.639.5274712184.7738.18532
#Mann= 3 , 0 , 0
9414.923  0.0727       09414.923  0.0727       012184.77  0.0727       0
#XS Ineff= 2 , 0
       09901.373        10439.41       0
Bank Sta=9414.923,12184.77
Exp/Cntr=0.3,0.1

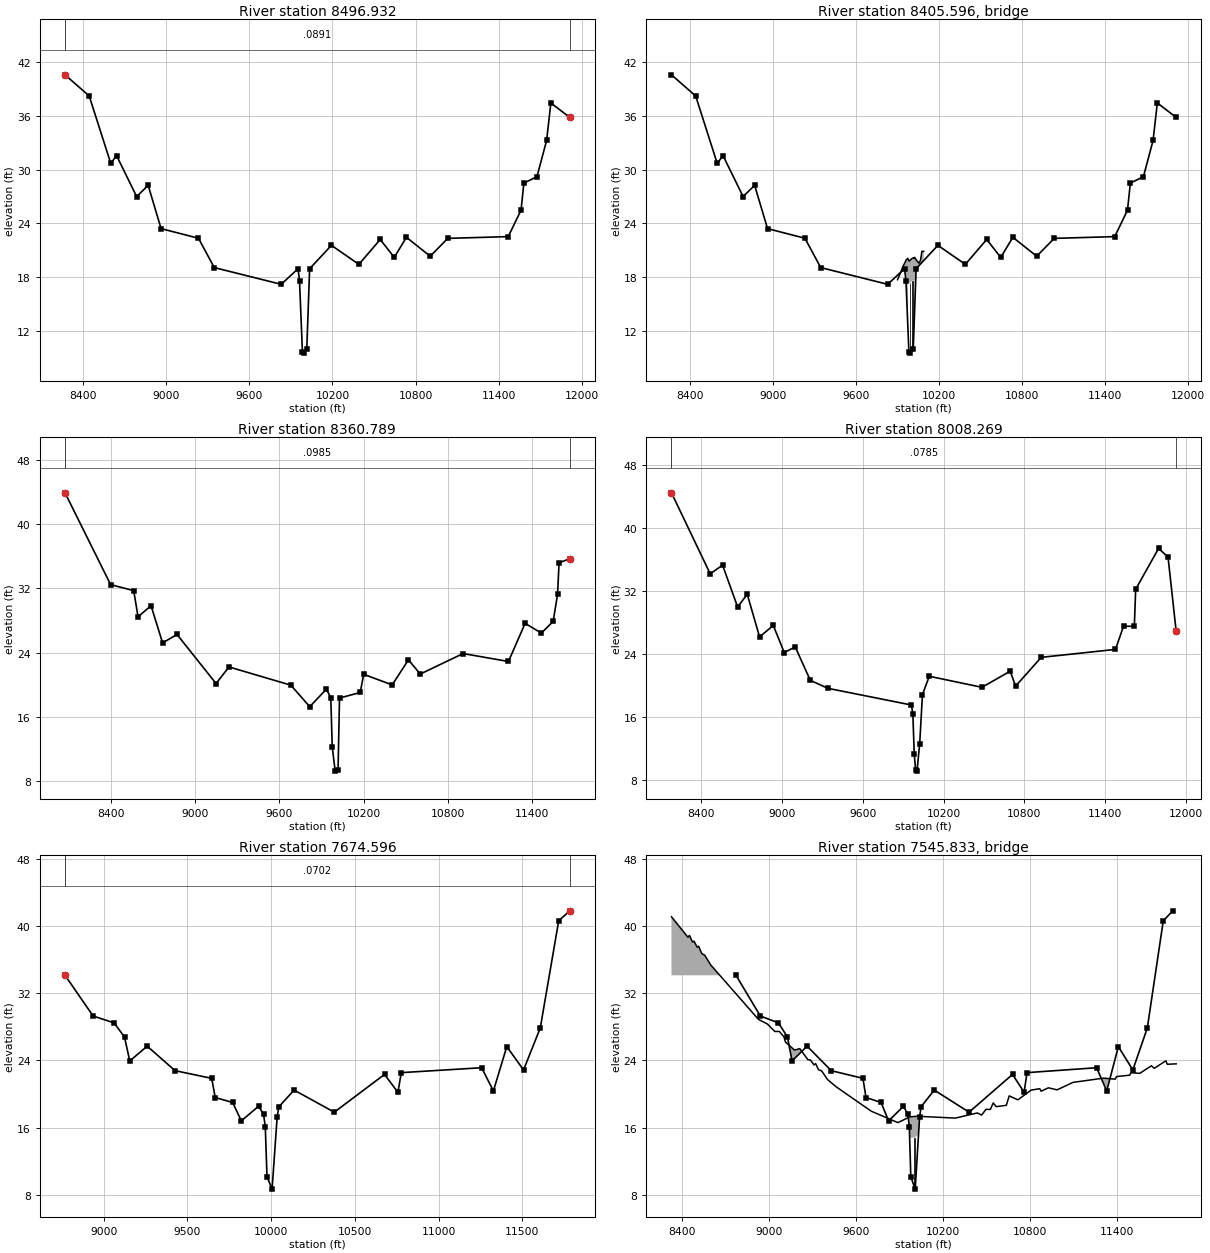
Type RM Length L Ch R = 1 ,8496.932,136.143500,136.143500,136.143500
XS GIS Cut Line= 6
778676.709226966863556.281780809780173.717389882863971.208556622
780325.944137871863629.819372639780579.856843174863423.913142219
781084.572523177863216.551602691781898.237743348 863015.75092648
#Sta/Elev= 30
8269.61840.573048444.25438.212158599.90930.687368641.41731.571848786.69526.99426
8869.71128.246078963.10523.418119232.90722.347579347.054 19.07379830.28617.20784
9952.01418.94962 9962.4817.574719983.413 9.68446 9993.879.53341610014.749.964072
10035.61 18.947410192.7721.5532910391.0619.4355210545.1422.2086410646.4820.20946
 10734.122.4495810906.21 20.341811032.8922.3329811469.2722.5281911561.6525.47793
11582.17 28.496511676.65 29.214211746.2833.2532211776.92 37.435311913.0335.82519
#Mann= 3 , 0 , 0
8269.618  0.0891       08269.618  0.0891       011913.03  0.0891       0
#XS Ineff= 2 , 0
       09707.811        10346.19       0
Bank Sta=8269.618,11913.03
Exp/Cntr=0.3,0.1

Type RM Length L Ch R = 3 ,8405.596,,,
BEGIN DESCRIPTION:
END DESCRIPTION:
Bridge Culvert--1,0,-1,-1, 0
Deck Dist Width WeirC Skew NumUp NumDn MinLoCord MaxHiCord MaxSubmerge Is_Ogee
46.571750,43.000000,2.6,0, 29, 29, , , 0.95, 0, 0,0,,
 9901.58 9911.77 9922.13 9932.49 9937.02 9942.85 9953.21 9963.58 9973.94 9975.18
 9975.25 9975.25 9984.30 9994.6610005.0210013.3410015.3910024.7510024.7510025.75
10036.1110046.4710051.5010056.8410067.2010077.5610087.9210089.6610090.47
   17.72   18.09   18.46   18.87   19.07   19.28   19.57   19.92   20.10   20.10
   20.10   20.10   19.80   19.92   20.08   20.14   20.11   20.20   20.20   20.21
   19.94   19.74   19.66   19.56   19.90   20.90   20.88   20.88   20.88
 -982.28 -981.91 -981.54 -981.13 -980.93 -980.72 -980.43 -980.08 -979.90 -979.90
 -979.90   17.60   17.30   17.42   17.58   17.64   17.61   17.70 -979.80 -979.79
 -980.06 -980.26 -980.34 -980.44 -980.10 -979.10 -979.12 -979.12 -979.12
 9901.58 9911.77 9922.13 9932.49 9937.02 9942.85 9953.21 9963.58 9973.94 9975.18
 9975.25 9975.25 9984.30 9994.6610005.0210013.3410015.3910024.7510024.7510025.75
10036.1110046.4710051.5010056.8410067.2010077.5610087.9210089.6610090.47
   17.72   18.09   18.46   18.87   19.07   19.28   19.57   19.92   20.10   20.10
   20.10   20.10   19.80   19.92   20.08   20.14   20.11   20.20   20.20   20.21
   19.94   19.74   19.66   19.56   19.90   20.90   20.88   20.88   20.88
 -982.28 -981.91 -981.54 -981.13 -980.93 -980.72 -980.43 -980.08 -979.90 -979.90
 -979.90   17.60   17.30   17.42   17.58   17.64   17.61   17.70 -979.80 -979.79
 -980.06 -980.26 -980.34 -980.44 -980.10 -979.10 -979.12 -979.12 -979.12
Pier Skew, UpSta & Num, DnSta & Num=  ,9991.42, 2 ,9991.42, 2 , 0 , 0 , 0 ,,
    2.00    2.00
 -980.12   19.88
    2.00    2.00
 -980.12   19.88
Pier Skew, UpSta & Num, DnSta & Num=  ,10008.58, 2 ,10008.58, 2 , 0 , 0 , 0 ,,
    2.00    2.00
 -979.90   20.10
    2.00    2.00
 -979.90   20.10
BR Coef=-1 , 0 , 0 ,, 0 ,,,0.8,0,1,0,
WSPro=,,,, 1 ,,,, 0 ,,,, 0 ,,,,-1 ,-1 ,-1 , 0 , 0 , 0 , 0 , 0
BC Design=,, 0 ,, 0 ,,,,,,

Type RM Length L Ch R = 1 ,8360.789,352.519300,352.519300,352.519300
XS GIS Cut Line= 6
778629.465218663863682.265803099780128.675083727864047.619467691
780286.155111581864050.769068241780387.938616246863793.978164434
780549.631367058863694.167824417781907.051991075863249.013708025
#Sta/Elev= 30
8072.32343.879298397.09232.452898561.77531.700688592.65328.444118685.28729.82811
8767.62825.195158870.55426.242879148.45620.13862 9241.0922.201349681.74719.93133
 9816.3117.250359934.74919.439639966.11818.381199976.49712.273279997.2549.231733
10018.019.40411510028.3918.3270910176.02 19.026910200.5721.2843310403.7419.96856
 10519.523.0876210603.6921.3153810908.8923.8704411232.3822.8802111350.89 27.6306
11466.6626.4166111550.8527.8754411582.4231.2636611592.9535.1898411668.7735.65669
#Mann= 3 , 0 , 0
8072.323  0.0985       08072.323  0.0985       011668.77  0.0985       0
#XS Ineff= 2 , 0
       09541.795        10301.28       0
Bank Sta=8072.323,11668.77
Exp/Cntr=0.3,0.1

Type RM Length L Ch R = 1 ,8008.269,333.673500,333.673500,333.673500
XS GIS Cut Line= 6
778632.614819199 863820.84822759780237.239843577864136.433137819
780344.231146574864138.789438173780640.808288306864185.706650361
781031.703557491864187.947191596782345.222401381864093.921175107
#Sta/Elev= 30
8177.47744.503828465.27234.193358556.99635.306868669.10329.972478740.44431.59921
8832.16826.170338934.08427.621989015.61624.181649097.14924.896079209.25620.63991
9339.03319.630419961.29617.500569971.45416.321849981.63711.294569991.8219.176663
10002.019.08809610022.3412.5870910042.6818.8230310093.5221.1596710484.8119.75357
10695.0321.80748 10735.119.9051910925.5923.5675711477.2124.5786411537.3527.53642
11617.5427.5150811627.5632.2285711797.9637.4380611868.1336.3082311928.4926.87499
#Mann= 3 , 0 , 0
8177.477  0.0785       08177.477  0.0785       011928.49  0.0785       0
#XS Ineff= 2 , 0
       09624.939        10562.08       0
Bank Sta=8177.477,11928.49
Exp/Cntr=0.3,0.1

Type RM Length L Ch R = 1 ,7674.596,220.343400,220.343400,220.343400
XS GIS Cut Line= 4
 779183.79491663864154.705886617780235.761502653 864460.21714066
780490.879147768864501.161947876782150.718641251864523.209151804
#Sta/Elev= 30
8769.38434.121198937.24929.278329062.20828.465439124.687 26.77429155.92623.93358
9260.05825.691739426.66922.779069645.346 21.86659666.17219.587779770.304 18.9954
 9822.3716.810179924.81218.545199955.196 17.60299965.32416.090159975.45210.16937
10005.848.69167610036.22 17.293410046.3518.4846710137.3220.4707910377.3417.84252
10677.3722.3339210757.3720.2051910777.3822.5459411257.4223.1292111327.4320.36767
11407.4325.6411211507.4422.8644611607.4527.8584311717.4640.6024311783.1841.78915
#Mann= 3 , 0 , 0
8769.384  0.0702       08769.384  0.0702       011783.18  0.0702       0
#XS Ineff= 2 , 0
       09681.849        10641.89       0
Bank Sta=8769.384,11783.18
Exp/Cntr=0.3,0.1

Type RM Length L Ch R = 3 ,7545.833,,,
BEGIN DESCRIPTION:
END DESCRIPTION:
Bridge Culvert--1,0,-1,-1, 0
Deck Dist Width WeirC Skew NumUp NumDn MinLoCord MaxHiCord MaxSubmerge Is_Ogee
54.671700,111.000000,2.6,0, 60, 60, , , 0.95, 0, 0,0,,
 8324.29 8437.92 8448.46 8469.53 8480.07 8501.14 8511.68 8532.75 8553.82 8595.96
 8924.35 8985.58 9037.57 9068.76 9100.03 9110.36 9172.75 9209.45 9266.33 9282.40
 9307.93 9318.87 9339.12 9359.92 9401.51 9463.90 9702.49 9886.64 9969.30 9969.30
10029.1610030.7010030.7010283.0610434.2410464.2710494.3110524.3510544.3710564.39
10634.4810654.5010714.5710804.6810864.7510874.7610924.8210984.8911095.0211305.22
11385.2311395.2311485.2511495.2511555.2611635.2711655.2711735.2811745.2811806.49
   41.08   38.65   38.87   38.07   38.18   37.47   37.58   36.72   36.50   35.33
   28.88   28.33   27.44   27.44   26.80   26.19   25.23   25.40   24.07   24.06
   23.46   23.62   22.88   22.76   21.71   20.82   17.96   16.60   17.29   17.29
   17.37   17.35   17.35   17.14   17.75   17.50   18.18   18.17   18.95   18.50
   18.66   19.78   19.31   20.46   20.64   20.34   20.74   20.50   21.39   21.89
   21.77   22.08   22.24   22.54   22.46   23.36   23.06   23.95   23.54   23.59
 -958.92 -961.35 -961.13 -961.93 -961.82 -962.53 -962.42 -963.28 -963.50 -964.67
 -971.12 -971.67 -972.56 -972.56 -973.20 -973.81 -974.77 -974.60 -975.93 -975.94
 -976.54 -976.38 -977.12 -977.24 -978.29 -979.18 -982.04 -983.40 -982.71   14.79
   14.87   14.85 -982.65 -982.86 -982.25 -982.50 -981.82 -981.83 -981.05 -981.50
 -981.34 -980.22 -980.69 -979.54 -979.36 -979.66 -979.26 -979.50 -978.61 -978.11
 -978.23 -977.92 -977.76 -977.46 -977.54 -976.64 -976.94 -976.05 -976.46 -976.41
 8324.29 8437.92 8448.46 8469.53 8480.07 8501.14 8511.68 8532.75 8553.82 8595.96
 8924.35 8985.58 9037.57 9068.76 9100.03 9110.36 9172.75 9209.45 9266.33 9282.40
 9307.93 9318.87 9339.12 9359.92 9401.51 9463.90 9702.49 9886.64 9969.30 9969.30
10029.1610030.7010030.7010283.0610434.2410464.2710494.3110524.3510544.3710564.39
10634.4810654.5010714.5710804.6810864.7510874.7610924.8210984.8911095.0211305.22
11385.2311395.2311485.2511495.2511555.2611635.2711655.2711735.2811745.2811806.49
   41.08   38.65   38.87   38.07   38.18   37.47   37.58   36.72   36.50   35.33
   28.88   28.33   27.44   27.44   26.80   26.19   25.23   25.40   24.07   24.06
   23.46   23.62   22.88   22.76   21.71   20.82   17.96   16.60   17.29   17.29
   17.37   17.35   17.35   17.14   17.75   17.50   18.18   18.17   18.95   18.50
   18.66   19.78   19.31   20.46   20.64   20.34   20.74   20.50   21.39   21.89
   21.77   22.08   22.24   22.54   22.46   23.36   23.06   23.95   23.54   23.59
 -958.92 -961.35 -961.13 -961.93 -961.82 -962.53 -962.42 -963.28 -963.50 -964.67
 -971.12 -971.67 -972.56 -972.56 -973.20 -973.81 -974.77 -974.60 -975.93 -975.94
 -976.54 -976.38 -977.12 -977.24 -978.29 -979.18 -982.04 -983.40 -982.71   14.79
   14.87   14.85 -982.65 -982.86 -982.25 -982.50 -981.82 -981.83 -981.05 -981.50
 -981.34 -980.22 -980.69 -979.54 -979.36 -979.66 -979.26 -979.50 -978.61 -978.11
 -978.23 -977.92 -977.76 -977.46 -977.54 -976.64 -976.94 -976.05 -976.46 -976.41
Pier Skew, UpSta & Num, DnSta & Num=  ,10000.00, 2 ,10000.00, 2 , 0 , 0 , 0 ,,
    3.00    3.00
 -982.84   17.16
    3.00    3.00
 -982.84   17.16
BR Coef=-1 , 0 , 0 ,, 0 ,,,0.8,0,1,0,
WSPro=,,,, 1 ,,,, 0 ,,,, 0 ,,,,-1 ,-1 ,-1 , 0 , 0 , 0 , 0 , 0
BC Design=,, 0 ,, 0 ,,,,,,

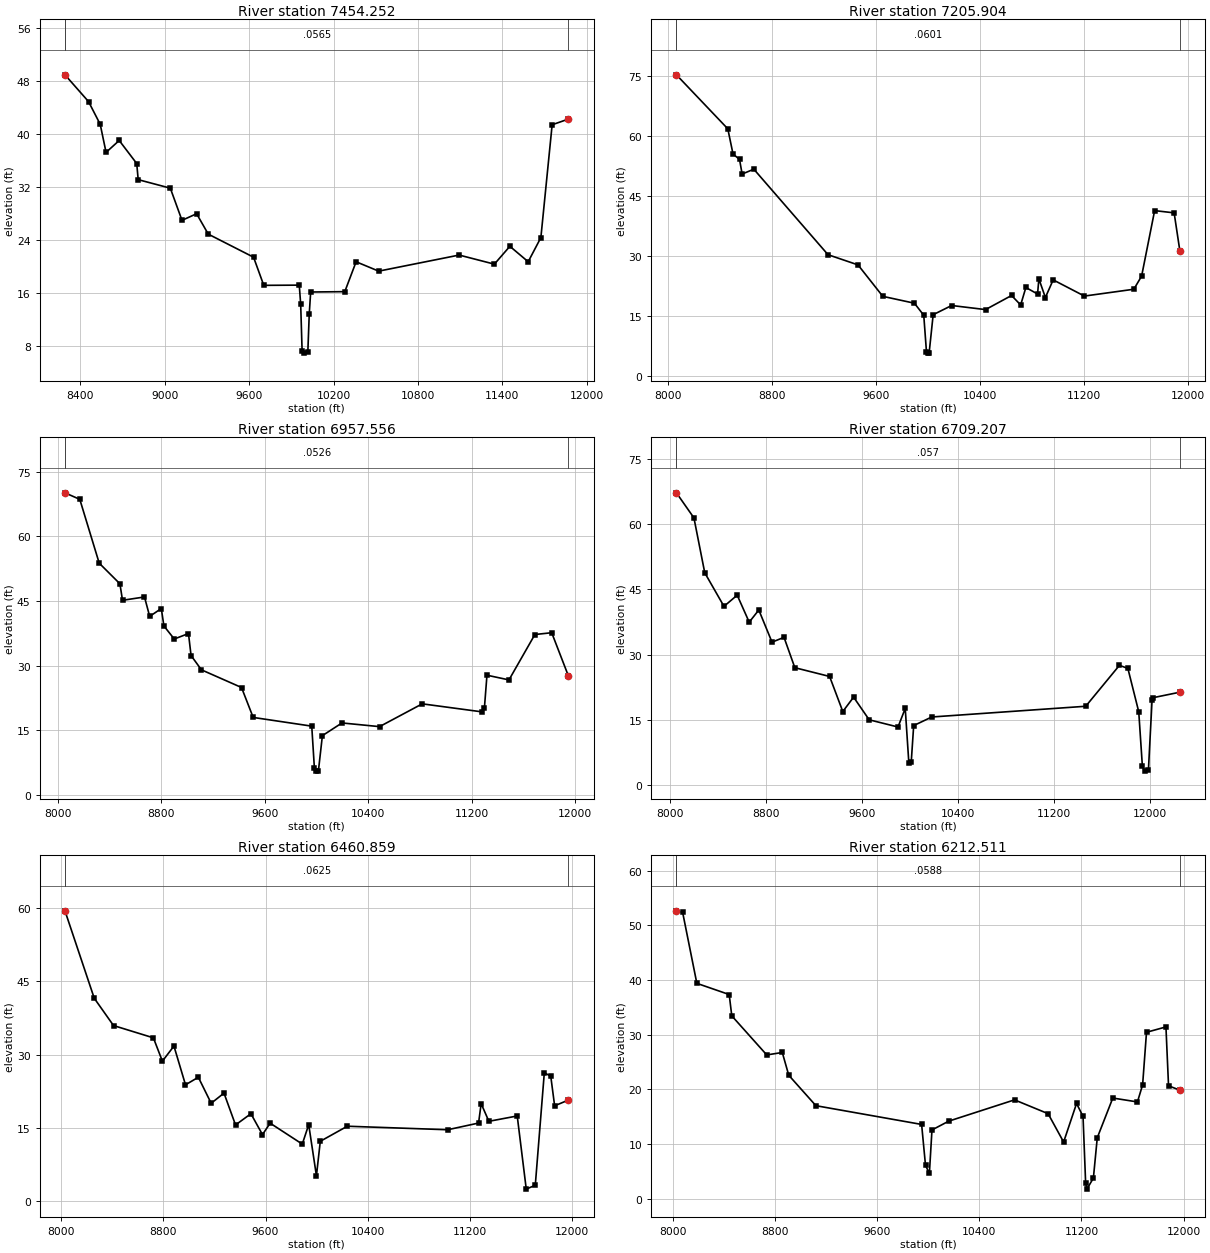
Type RM Length L Ch R = 1 ,7454.252,248.348400,248.348400,248.348400
XS GIS Cut Line= 6
 778673.55962643864280.689908907780057.131399482864666.417390779
780238.798844278864683.533787593780704.789861768864748.907835469
781377.837693602864805.504314527782190.359399468864852.607022122
#Sta/Elev= 30
8290.40848.888068458.00544.853798541.056 41.42438582.58137.193938676.01338.99238
8800.58935.515868810.97133.086859039.36131.801419122.41126.952379226.22527.94917
9309.27624.872629631.09821.397929703.76717.154259956.09617.185629966.22514.26714
9976.3567.2118429986.4936.93629310016.917.06414110027.0412.8342910037.1816.15017
10279.7716.2028710360.1520.7072310520.7419.2948211092.6821.71933 11343.1 20.3482
11453.2923.04024 11583.520.7112311673.6524.3519311753.7941.3608111869.3442.21696
#Mann= 3 , 0 , 0
8290.408  0.0565       08290.408  0.0565       011869.34  0.0565       0
#XS Ineff= 2 , 0
       09701.582        10693.75       0
Bank Sta=8290.408,11869.34
Exp/Cntr=0.3,0.1

Type RM Length L Ch R = 1 ,7205.904,248.348400,248.348400,248.348400
XS GIS Cut Line= 6
778409.728561384865067.123782162779091.579942162865058.004560072
779812.045764303865020.603721011780475.105172145864912.069744313
 780687.49176704864894.965622478782268.879066972864917.131660624
#Sta/Elev= 30
8064.33475.282468459.61761.772078499.62455.46964 8549.6454.127348569.64650.45913
8659.67551.676699230.24330.282369460.69127.735289651.45119.867199894.40618.14868
9966.39215.138669987.0596.0571679997.3925.66160410007.735.68967410038.6915.27555
10181.0117.5747510441.5616.5523910641.5720.0819210711.5717.7132910751.5822.08426
 10841.620.44696 10851.624.2523210901.6119.5750710961.6223.9849511201.6619.93613
11581.7321.6422911641.7424.9291211741.76 41.313611891.7940.7509211935.6731.27671
#Mann= 3 , 0 , 0
8064.334  0.0601       08064.334  0.0601       011935.67  0.0601       0
#XS Ineff= 2 , 0
       0                10687.46       0
Bank Sta=8064.334,11935.67
Exp/Cntr=0.3,0.1

Type RM Length L Ch R = 1 ,6957.556,248.348400,248.348400,248.348400
XS GIS Cut Line= 6
778460.343589728 865230.20339373 779820.73753724865242.802415524
780217.831255008865214.379959136780568.469919726 865153.09017131
 780829.56656881865139.650371805782343.817262341865198.902334157
#Sta/Elev= 30
8053.83170.076198168.55568.566598318.64253.761338478.73548.97564 8498.7445.14855
8668.76945.924148708.77541.417028798.78243.240658818.78239.200938898.78236.17217
9008.78237.434329028.78332.336989108.78729.024449418.87924.922219509.00917.98046
9961.90815.95897 9982.426.1788259992.7545.52634810013.425.59574410044.1813.75929
10195.68 16.702710486.0215.8467710816.1221.1338911276.5119.2796911296.5320.06159
11316.5527.7743311486.7526.6842611687.0137.2113411817.1837.6297211946.1727.61083
#Mann= 3 , 0 , 0
8053.831  0.0526       08053.831  0.0526       011946.17  0.0526       0
#XS Ineff= 2 , 0
       0                 10607.9       0
Bank Sta=8053.831,11946.17
Exp/Cntr=0.3,0.1

Type RM Length L Ch R = 1 ,6709.207,248.348400,248.348400,248.348400
XS GIS Cut Line= 6
778449.179041237865341.487890795779256.478769958865389.444600478
780241.092491597865414.191537857781810.695849329865541.419343755
782254.773037672865583.504606754782635.063296288865631.251255095
#Sta/Elev= 30
8051.38867.156838197.52861.396338287.72548.789948448.07641.079148558.25243.65102
8658.38537.447768738.49240.244458848.63832.852638948.70533.964729038.75726.99034
9328.841 24.97729438.85516.918219528.86620.224749658.88315.020139899.18813.36503
9959.46617.637579989.6415.07994410009.76 5.4267410029.8813.6905710180.6115.66581
11464.4818.1297911745.7327.5352211816.0526.8211311906.5916.8648411936.824.407499
11956.983.23085111987.213.41466412017.4519.4755912027.53 20.108912249.3221.35961
#Mann= 3 , 0 , 0
8051.388   0.057       08051.388   0.057       012249.32   0.057       0
#XS Ineff= 2 , 0
       0                10557.53       0
Bank Sta=8051.388,12249.32
Exp/Cntr=0.3,0.1

Type RM Length L Ch R = 1 ,6460.859,248.348400,248.348400,248.348400
XS GIS Cut Line= 6
778407.435818924865484.294193617779231.693180474865573.424817491
780005.004340837865637.865945049780226.916471274 865659.59322776
781451.703581364865798.059962975782321.754421827865910.345156951
#Sta/Elev= 30
8031.04859.470388259.99541.562788410.90635.960228722.70533.444368793.07228.66334
8883.51831.758838973.88623.816779074.29625.370089174.67620.036279274.98822.11509
 9365.2715.591939485.64517.894389575.92613.615479636.11415.954879887.35211.66976
9937.66815.659799998.0475.17358510028.2412.2436710239.5815.3324811024.5514.60971
11266.3415.98221 11286.519.9636811346.9716.3391211568.7217.4330911639.332.441882
11709.953.24527711780.5626.28549   11831 25.582711861.2619.5168911968.9520.68946
#Mann= 3 , 0 , 0
8031.048  0.0625       08031.048  0.0625       011968.95  0.0625       0
#XS Ineff= 2 , 0
       0                10543.15       0
Bank Sta=8031.048,11968.95
Exp/Cntr=0.3,0.1

Type RM Length L Ch R = 1 ,6212.511,248.348400,248.348400,248.348400
XS GIS Cut Line= 6
778387.002607447865630.922451249779486.356309141865807.381804473
 780196.04189293865900.273214584780450.495210389865939.731718784
 781247.08672429866049.862202007782282.237659356866221.601701871
#Sta/Elev= 30
8029.91252.631878078.49952.363838189.84839.36849 8443.0537.32297 8463.3233.42192
8736.96326.275988858.58226.72478 8909.1922.558179121.73216.992589949.09813.56386
9979.4486.07767510009.814.61144210030.0612.55515 10161.514.1684310676.1518.06003
10938.9215.5316211060.4610.3470511161.7417.3967611212.3815.0265211232.632.911325
11242.761.733121 11293.43.75556411323.7911.1247711445.3718.3935311638.1217.67986
 11678.720.8046611709.1330.41814 11861.331.4004811881.5920.6372711970.0919.82642
#Mann= 3 , 0 , 0
8029.912  0.0588       08029.912  0.0588       011970.09  0.0588       0
#XS Ineff= 2 , 0
       0                10509.36       0
Bank Sta=8029.912,11970.09
Exp/Cntr=0.3,0.1

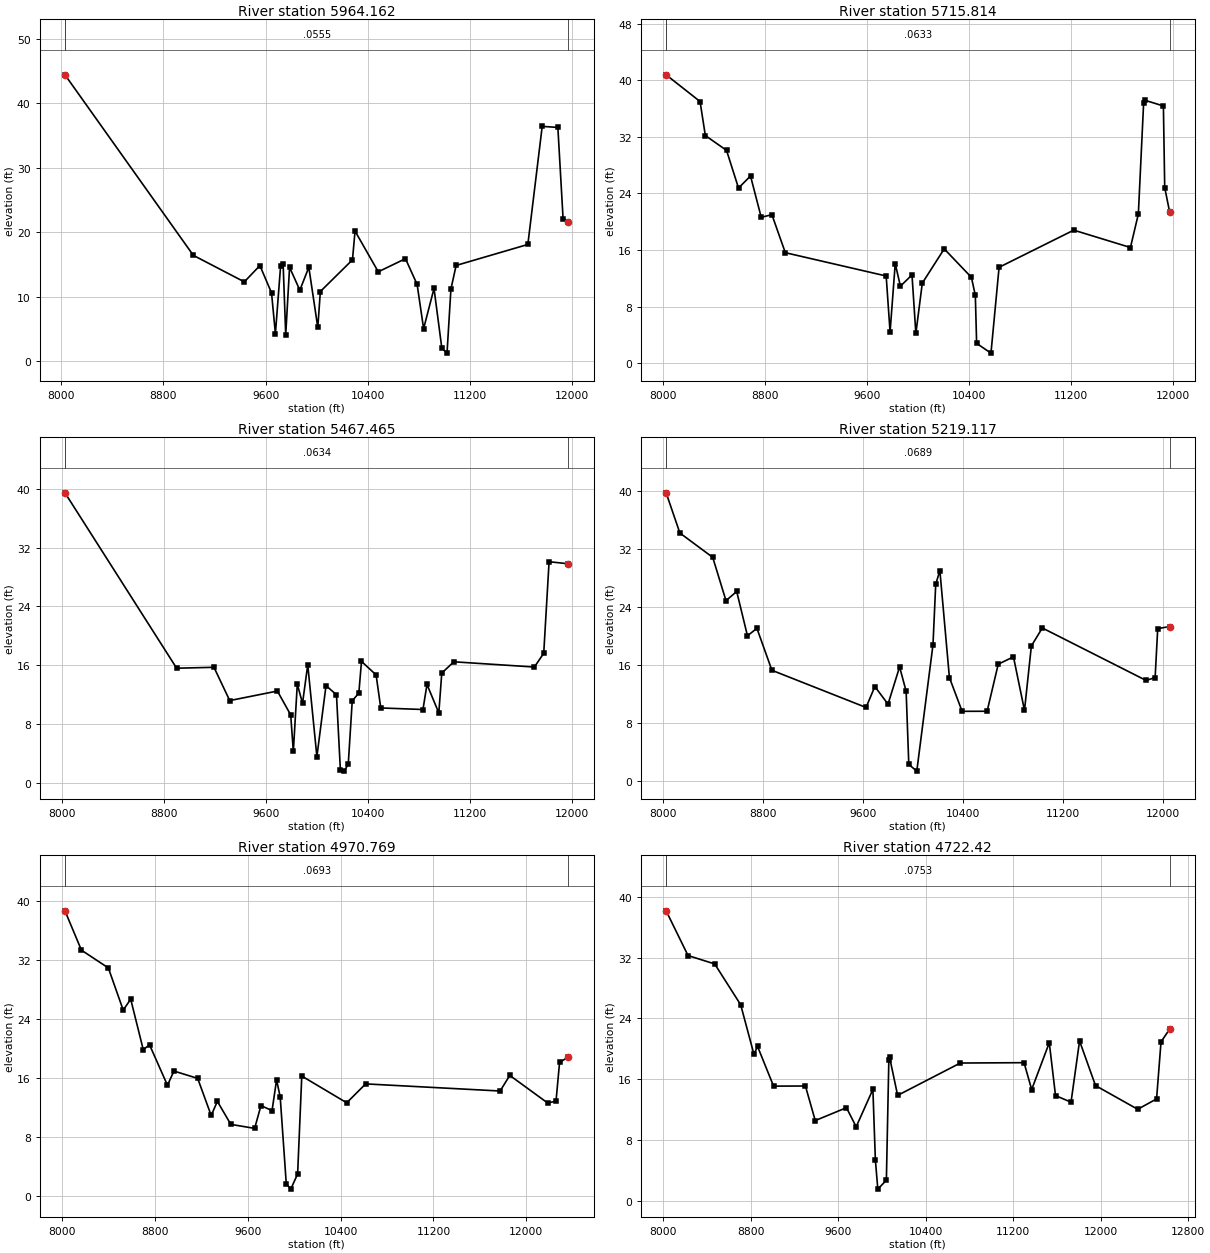
Type RM Length L Ch R = 1 ,5964.162,248.348300,248.348300,248.348300
XS GIS Cut Line= 6
778375.006723348865785.676717868779778.843900564866100.887652601
780058.889491728866144.388987139780508.029617678866186.582690681
780890.838499468866241.575596189782246.277083668866511.519802397
#Sta/Elev= 30
8028.78444.394189033.81916.434759433.193 12.32839555.13314.852549646.23310.62168
 9676.534.2882869716.92614.708569737.12415.026869757.2984.1339719787.47414.58381
9867.94611.038049938.21214.5918810008.435.261426 10028.510.8349110279.93 15.7405
10300.0920.1925810481.9713.8850710694.8515.9203410786.2411.9294610837.02 5.07934
10918.4911.3111910979.582.06389311020.321.29052111050.8711.2175411091.6214.87106
11653.1918.1218611765.5836.4109811888.1836.2465911929.0522.1308211971.2321.64488
#Mann= 3 , 0 , 0
8028.784  0.0555       08028.784  0.0555       011971.23  0.0555       0
#XS Ineff= 2 , 0
       0                10428.07       0
Bank Sta=8028.784,11971.23
Exp/Cntr=0.3,0.1

Type RM Length L Ch R = 1 ,5715.814,248.348400,248.348400,248.348400
XS GIS Cut Line= 6
778377.025366166865910.195812384 778950.21617533866063.111682096
779847.267450536866339.957928551780056.622005438866382.940756044
780848.872089969866511.771147134782202.233283135866852.897883457
#Sta/Elev= 30
8027.64140.758448293.52636.983418334.86132.172268500.93730.077028594.69924.75325
8688.80626.452558772.57620.612998856.34520.984438961.44715.609549751.68812.31232
9782.1574.3907839822.63214.069329863.10710.869529953.93212.466279984.199 4.18664
10034.64 11.304510206.3516.1493510419.5312.1213510450.159.57034610460.362.785393
10572.661.40727110636.27 13.544211221.2918.7967711665.3916.3410811727.3621.07798
11768.6736.75681   1177937.1631511923.5936.3522911933.9224.8186511972.3721.37763
#Mann= 3 , 0 , 0
8027.641  0.0633       08027.641  0.0633       011972.37  0.0633       0
#XS Ineff= 2 , 0
       09044.315        10335.74       0
Bank Sta=8027.641,11972.37
Exp/Cntr=0.3,0.1

Type RM Length L Ch R = 1 ,5467.465,248.348400,248.348400,248.348400
XS GIS Cut Line= 6
778384.115914501  866009.0231165 778679.02257111866093.305114408
779070.191874686866226.753115883779952.059780103866587.057415196
780702.123289838866776.204496304782129.905381872867238.692302085
#Sta/Elev= 30
8026.16139.464758901.706 15.59099194.37315.713479317.97511.184129691.62112.48177
9796.0359.2316859816.7014.252495  9847.713.415059888.748 10.81989929.68816.05641
10001.343.54734710072.9313.2223810154.9111.9763910185.741.68444910216.581.580022
 10247.52.57609710278.5311.1519710330.2512.2033310351.0616.5160610465.5914.67987
10502.1610.1806410833.03 9.9680110864.6313.3780710957.329.50483710980.4914.93002
11075.28 16.463911706.4915.7498411779.9117.6207311821.8630.0877111973.8529.80376
#Mann= 3 , 0 , 0
8026.161  0.0634       08026.161  0.0634       011973.85  0.0634       0
#XS Ineff= 2 , 0
       08983.051        10254.41       0
Bank Sta=8026.161,11973.85
Exp/Cntr=0.3,0.1

Type RM Length L Ch R = 1 ,5219.117,248.348400,248.348400,248.348400
XS GIS Cut Line= 6
778389.729220629866076.430475533779180.545951158866361.658978269
780076.843128115866859.858928576781189.157982379867366.813771471
781819.194052666867624.613030121782067.149689198867689.712995246
#Sta/Elev= 30
 8026.1839.799198136.098 34.24198398.97330.872288505.10724.879798590.76126.15156
 8676.7920.023688752.44621.051728872.49615.249459625.452  10.1079696.00313.00095
9801.184  10.563  9893.915.719779946.19612.346049967.5512.22398910031.45 1.30016
10161.0418.7858210182.8827.1611210216.2129.0356710292.37 14.2465   103949.572975
10594.019.58259710682.9116.0940210804.83 17.107910893.03 9.7039510948.0118.61491
11035.6521.1039711865.7213.8469611938.0914.2418611958.7721.0139412054.0421.29908
#Mann= 3 , 0 , 0
 8026.18  0.0689       0 8026.18  0.0689       012054.04  0.0689       0
#XS Ineff= 2 , 0
       0 8943.33         10206.9       0
Bank Sta=8026.18,12054.04
Exp/Cntr=0.3,0.1

Type RM Length L Ch R = 1 ,4970.769,248.348400,248.348400,248.348400
XS GIS Cut Line= 6
778349.541344523 866104.01603359779612.463452667866666.805929214
780299.638444602867408.603063062780844.594856858867791.033094972
781419.765196592868091.054481462782019.670628279868225.548111066
#Sta/Elev= 30
8026.22438.674238167.83733.346978400.00130.93548 8527.9625.218318592.42526.70639
8700.608  19.869 8754.9320.52032 8909.2415.035418964.82216.968749169.434 15.9716
9285.89210.945069338.99212.858479454.9459.7421649660.1779.1990329714.69212.29125
9810.01711.598539849.031 15.76479880.22813.468859932.5651.7112329971.2780.969156
 10030.43.01761710066.1916.2893410453.31 12.6671 10616.515.2270711774.6414.26223
11858.2416.3771612184.57 12.637712256.3112.8878512287.0518.1535712363.5818.86371
#Mann= 3 , 0 , 0
8026.224  0.0693       08026.224  0.0693       012363.58  0.0693       0
#XS Ineff= 2 , 0
       08965.586        10223.53       0
Bank Sta=8026.224,12363.58
Exp/Cntr=0.3,0.1

Type RM Length L Ch R = 1 , 4722.42,248.348400,248.348400,248.348400
XS GIS Cut Line= 6
778193.790559918866160.441705897 779398.58915326 866708.15925476
 780047.34458065867556.254785582780702.666411132868056.749936938
781160.278235883868311.327188805 781992.53973639868456.160692558
#Sta/Elev= 30
8026.21738.180878226.55432.286818470.361 31.18268708.05825.79945    882919.27573
8862.154 20.31249008.544 15.08239299.71315.098969389.65610.54385 9674.8912.24165
9763.8919.7251629916.59514.652189939.2355.3626519961.6131.51110410039.862.686393
10062.3818.5256610069.0818.8954910142.6513.8626910715.8518.1266311298.5218.17219
11368.3114.6333311529.2420.8034111586.2313.8399211728.0512.9658411806.0921.03675
11951.8615.1551312337.5712.0321412510.1313.3966612550.7320.9134412629.4422.58932
#Mann= 3 , 0 , 0
8026.217  0.0753       08026.217  0.0753       012629.44  0.0753       0
#XS Ineff= 2 , 0
       09077.733        10302.52       0
Bank Sta=8026.217,12629.44
Exp/Cntr=0.3,0.1

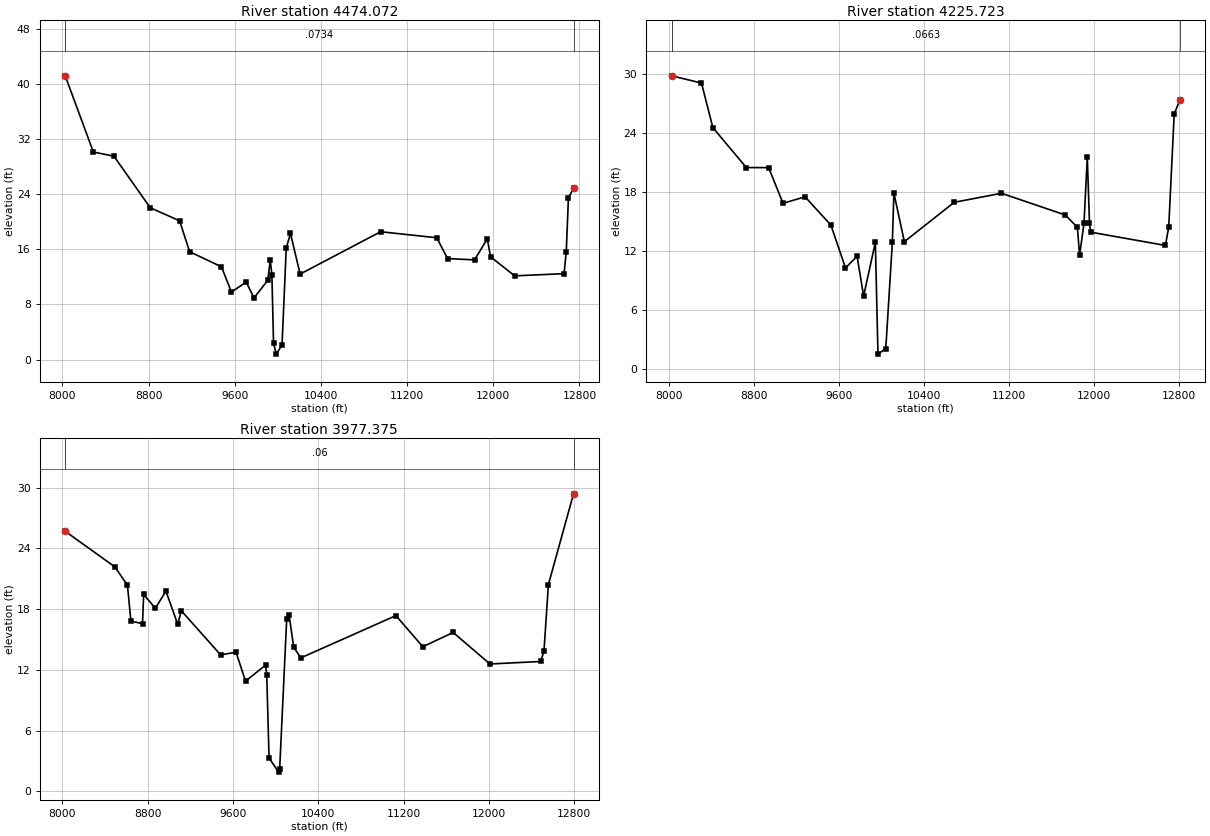
Type RM Length L Ch R = 1 ,4474.072,248.348400,248.348400,248.348400
XS GIS Cut Line= 6
777927.752713263866323.320183426779083.670080245866845.912336215
780021.187254131867773.545839518780806.194985032868301.966597766
 781056.08689338868437.965791702781931.495229483868605.380598247
#Sta/Elev= 30
8026.17241.210558287.61230.141248478.33529.541388816.38522.041489087.97620.15674
 9181.5515.663029476.91313.472129569.0929.810764 9706.6411.245139779.0048.961966
9906.75611.497519929.94414.44599 9945.1812.265359960.4162.3422579986.2820.788435
 10039.22.13207310078.5116.2150410117.8118.3141110206.9412.4147410954.68 18.5657
11475.6817.6899211576.06  14.66611826.8214.4788511944.8517.5257311975.3914.91928
12199.38 12.155812657.5312.47682 12677.915.5972412698.2623.48905 12745.624.86668
#Mann= 3 , 0 , 0
8026.172  0.0734       08026.172  0.0734       0 12745.6  0.0734       0
#XS Ineff= 2 , 0
       09239.125        10358.87       0
Bank Sta=8026.172,12745.6
Exp/Cntr=0.3,0.1

Type RM Length L Ch R = 1 ,4225.723,248.348300,248.348300,248.348300
XS GIS Cut Line= 6
777680.124430418866600.227089569 778257.09501949866816.667673692
778784.553994954867081.987728179780138.597861946868033.259900197
780853.437951297 868469.53885965781897.581614554868747.817780927
#Sta/Elev= 30
8026.14229.76497 8306.5429.028858413.47324.505198727.94820.448478938.44520.43494
9073.54516.812669280.47317.47453 9523.6614.60238 9660.7310.250649770.361 11.4312
9831.6397.3789819941.94112.856929966.4531.49132610040.122.06007210101.8812.85923
10116.2117.8632110214.5412.9138310683.79 16.915711128.3417.83361 11728.415.62554
11842.2414.3671411862.9411.5357911904.3314.7685811935.3821.5004611956.0814.76394
11966.4313.8840912670.16  12.53412701.2114.3849312752.9625.8892112807.3727.35101
#Mann= 3 , 0 , 0
8026.142  0.0663       08026.142  0.0663       012807.37  0.0663       0
#XS Ineff= 2 , 0
       0                10355.53       0
Bank Sta=8026.142,12807.37
Exp/Cntr=0.3,0.1

Type RM Length L Ch R = 1 ,3977.375,0.000000,0.000000,0.000000
XS GIS Cut Line= 6
 777499.53306368866919.994447872778201.382893592867194.184553459
779525.600574046867829.712270513780496.931426644  868416.6910166
780842.822462291868609.987801626781822.971661747868869.906794652
#Sta/Elev= 30
8026.14925.683918490.63922.177398609.88920.362348642.50616.794788751.22816.56873
  8762.119.441918871.69818.075338971.08719.769759081.677 16.49069115.15117.83548
  9483.5 13.47929628.60713.729469717.77710.879529905.29912.46004 9916.33 11.5319
9938.3913.277092 10028.71.88990610037.662.16051910103.8417.0217710125.8917.43801
10169.4514.2200810237.0613.1801911128.3617.3522211380.7614.2769711665.25 15.6878
12010.1512.5723712486.0512.8201912517.0813.8368612558.4720.4162112794.3229.38263
#Mann= 3 , 0 , 0
8026.149    0.06       08026.149    0.06       012794.32    0.06       0
#XS Ineff= 2 , 0
       0                10304.74       0
Bank Sta=8026.149,12794.32
Exp/Cntr=0.3,0.1